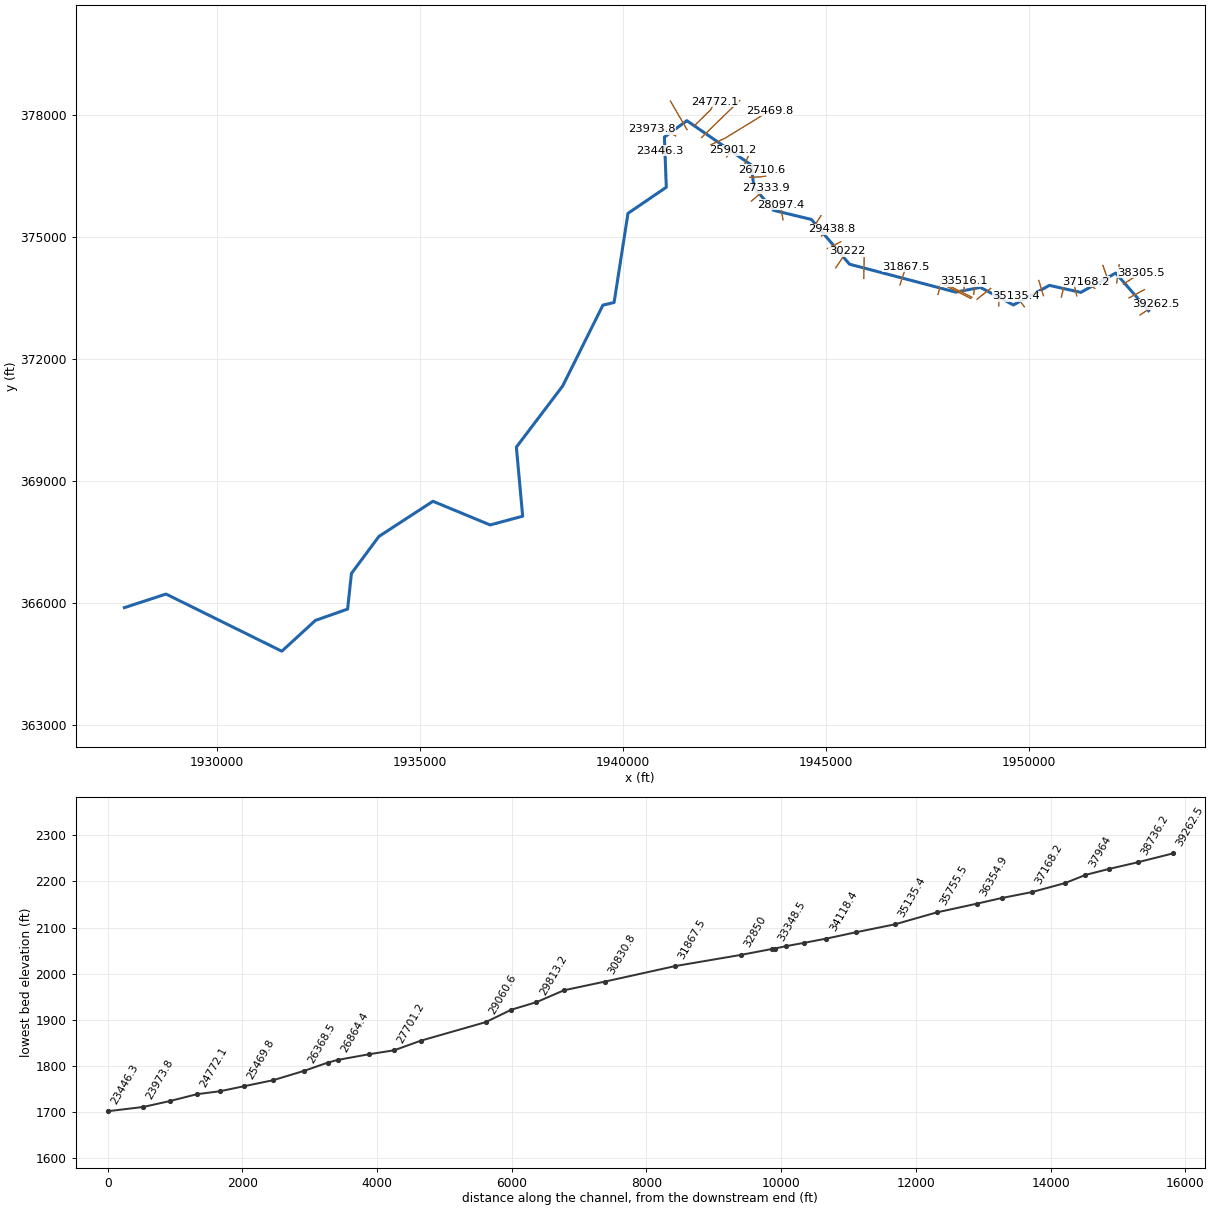
--- ROARINGCK.prj (project) ---

Proj Title=ROARINGCK
Current Plan=p01
Default Exp/Contr=0,0
English Units
Geom File=g01
Flow File=f01
Plan File=p01
BEGIN DESCRIPTION:
END DESCRIPTION:
DSS Export Rating Curves= 0
DSS Export Rating Curve Sorted= 0
DSS Export Volume Flow Curves= 0
DXF OffsetX= 0
DXF OffsetY= 0
DXF ScaleX= 0
DXF ScaleY= 0

--- ROARINGCK.p01 (plan) ---

Plan Title=Floodplain
Program Version=4.00
Geom File=g01
Flow File=f01
K Sum by GR=0
Std Step Tol=0.01
Critical Tol=0.01
Num of Std Step Trials=20
Max Error Tol=0.3
Flow Tol Ratio=0.001
Split Flow NTrial=30
Split Flow Tol=0.02
Split Flow Ratio=0.02
Log Output Level=0
Friction Slope Method=1
Unsteady Friction Slope Method=2
Unsteady Bridges Friction Slope Method=1
Global Log Level=0
CheckData=False
Run HTab=0
Run UNet=0
Run PostProcess=0
UNET Theta=0
UNET Theta Warmup=0
UNET ZTol=0
UNET ZSATol=0
UNET MxIter=0
UNET MaxInSteps=0
UNET DtIC=0
UNET DtMin=0
UNET MaxCRTS=0
UNET WFStab=0
UNET SFStab=0
UNET WFX=0
UNET SFX=0
UNET DSS MLevel=0
UNET DZMax Abort=0
UNET Convert EG Bridges=0
UNET Use Existing IB Tables=0
UNET Froude Limit=0
UNET Froude Power=0
Write IC File=0
Echo Input=False
Echo Output=False
Write Detailed=0

--- ROARINGCK.f01 (steady flow) ---

Flow Title=NFF Regression Equation
Program Version=4.10
Number of Profiles= 1
Profile Names=P100yr
River Rch & RM=ROARINGCK,Main            ,39262.5
  550.76
River Rch & RM=ROARINGCK,Main            ,37964
  592.25
River Rch & RM=ROARINGCK,Main            ,35755.5
652.9716
River Rch & RM=ROARINGCK,Main            ,34118.4
711.1508
River Rch & RM=ROARINGCK,Main            ,30222
  774.93
River Rch & RM=ROARINGCK,Main            ,29813.2
   916.6
River Rch & RM=ROARINGCK,Main            ,25469.8
 1009.31
River Rch & RM=ROARINGCK,Main            ,25115.4
1857.517
River Rch & RM=ROARINGCK,Main            ,18191.8
1976.402
River Rch & RM=ROARINGCK,Main            ,12934.6
2109.243
River Rch & RM=ROARINGCK,Main            ,8596.3
2336.023
River Rch & RM=ROARINGCK,Main            ,5910.8
2428.444
River Rch & RM=ROARINGCK,Main            ,223.4
2644.635
Boundary for River Rch & Prof#=ROARINGCK,Main            , 1
Up Type= 0
Dn Type= 3
Dn Slope=0.01214
DSS Import GetInterval= 0
DSS Import GetPeak= 0
DSS Import FillOption= 0

--- ROARINGCK.g01 (geometry) ---

Geom Title=USGS 10m DEM
Program Version=4.10

River Reach=ROARINGCK       ,Main
Reach XY= 30
     1952948.614      373190.351     1952139.198      374116.633
     1951279.612      373641.077     1950505.516      373813.303
      1949619.73      373332.182     1948806.518      373763.761
     1948202.792       373647.38     1945585.192      374334.513
     1944646.402      375436.818     1943716.107      375661.124
     1943231.732      376224.058     1943164.457      376779.613
     1941579.283      377868.919     1941026.303        377465.4
     1941073.016      376229.362     1940129.425      375587.356
      1939787.65      373392.119     1939513.059      373327.445
     1938520.947      371335.967     1937381.449      369831.002
     1937536.433      368130.021     1936735.536      367914.519
       1935327.4      368497.553     1933995.721      367630.826
     1933319.945      366719.569     1933225.526      365842.757
     1932432.896      365563.787     1931606.021      364805.401
     1928754.734      366212.795      1927729.15      365878.373

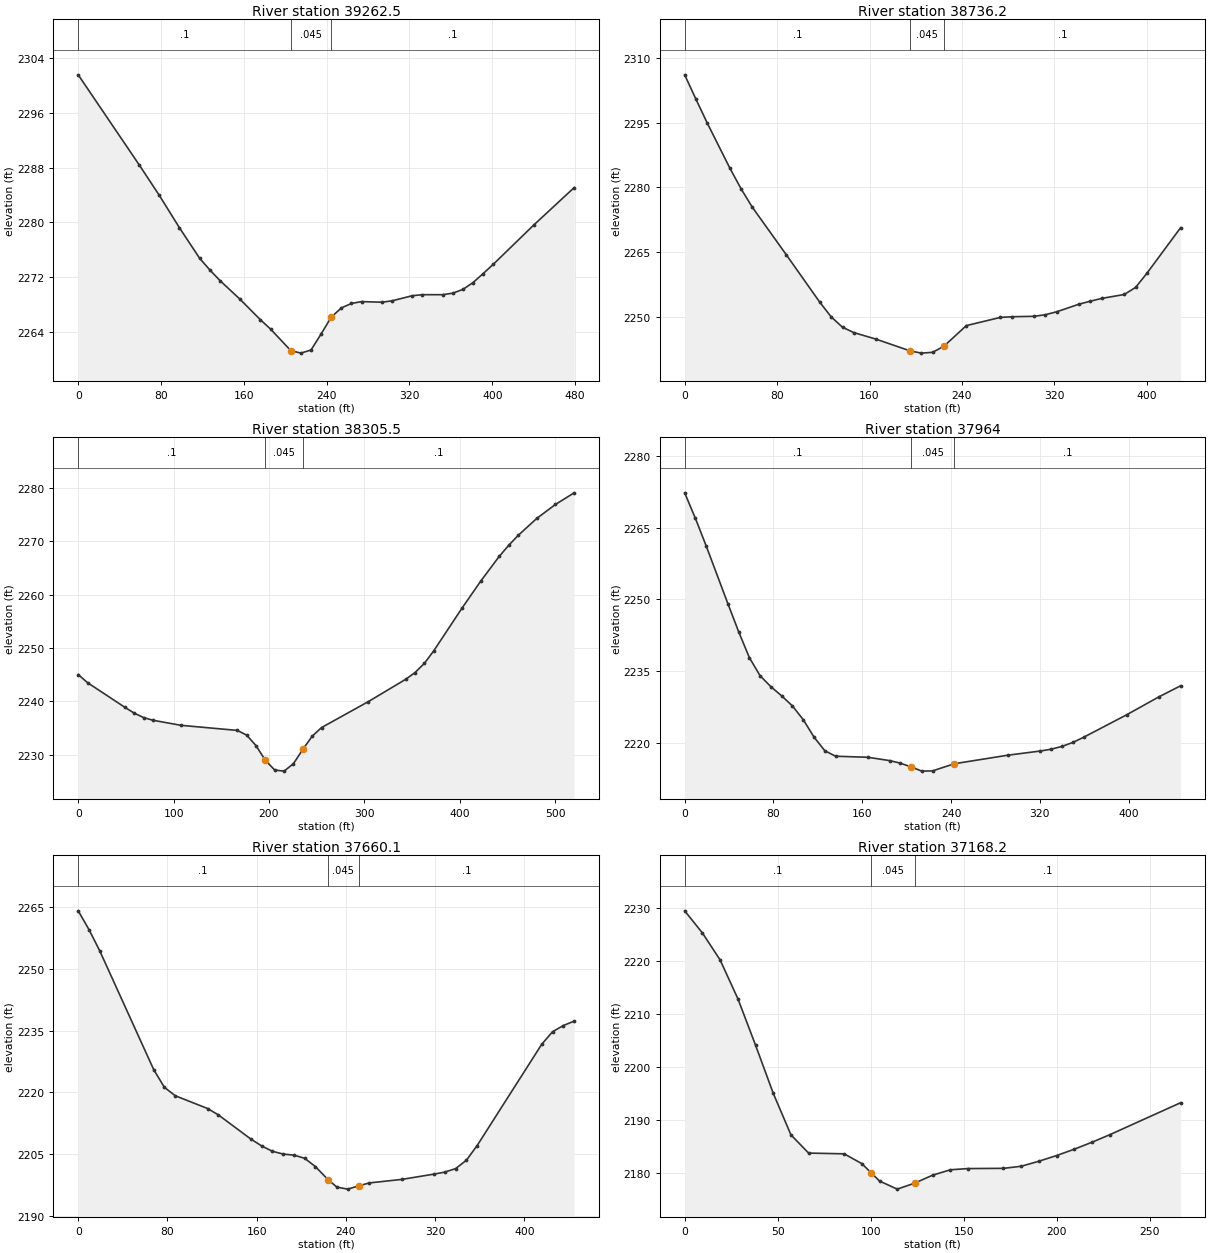
Type RM Length L Ch R = 1 ,39262.5 ,526.8,526.2,525.4
XS GIS Cut Line= 2
     1952736.793      373083.515     1953136.099      373348.272
#Sta/Elev= 30
       0 2301.56    58.7 2288.45    78.2 2283.98    97.8 2279.21   117.3 2274.75
   127.1 2273.06   136.9  2271.5   156.4 2268.75     176 2265.77   185.8 2264.41
   205.3 2261.27   215.1 2260.89   224.9 2261.35   234.7  2263.7   244.4 2266.14
   254.2  2267.5     264 2268.15   273.8 2268.42   293.3 2268.33   303.1 2268.53
   322.7 2269.28   332.4 2269.43     352 2269.43   361.8 2269.65   371.6  2270.2
   381.3 2271.19   391.1  2272.5   400.9 2273.86     440  2279.6   479.1 2285.08
#Mann= 3 , 0 , 0
       0      .1       0   205.3    .045       0   244.4      .1       0
Bank Sta=205.3,244.4
XS Rating Curve= 0 ,0
Exp/Cntr=0.3,0.1

Type RM Length L Ch R = 1 ,38736.2 ,428.5,430.7,432.8
XS GIS Cut Line= 2
     1952467.696      373504.522       1952845.3      373708.515
#Sta/Elev= 29
       0 2306.16     9.8 2300.47    19.5 2294.98      39 2284.54    48.8 2279.69
    58.5 2275.43    87.8 2264.42     117 2253.32   126.8 2249.94   136.6 2247.53
   146.3  2246.3   165.8 2244.75   195.1 2242.04   204.8 2241.52   214.6 2241.71
   224.4 2243.14   243.8 2247.92   273.1 2249.81   282.9 2249.97   302.4 2250.07
   312.1 2250.44   321.9 2251.12   341.4  2252.9   351.2 2253.59   360.9 2254.23
   380.4 2255.14   390.2 2256.78   399.9 2260.02   429.2 2270.66
#Mann= 3 , 0 , 0
       0      .1       0   195.1    .045       0   224.4      .1       0
Bank Sta=195.1,224.4
XS Rating Curve= 0 ,0
Exp/Cntr=0.3,0.1

Type RM Length L Ch R = 1 ,38305.5 ,321.9,341.5,360.9
XS GIS Cut Line= 2
     1952328.807      373843.064     1952762.835      374129.522
#Sta/Elev= 30
       0 2245.03     9.8  2243.5    49.1 2238.86    58.9 2237.77    68.7 2236.95
    78.5 2236.45   107.9  2235.5   166.8 2234.55   176.6 2233.67   186.4  2231.7
   196.2 2228.94     206 2227.12   215.9 2226.91   225.7 2228.32   235.5 2230.98
   245.3 2233.46   255.1 2235.08   304.2 2239.95   343.4 2244.14   353.2 2245.41
     363 2247.13   372.9 2249.51   402.3 2257.46   421.9 2262.52   441.5 2267.21
   451.4 2269.27   461.2 2271.12   480.8 2274.32   500.4 2276.94     520 2279.12
#Mann= 3 , 0 , 0
       0      .1       0   196.2    .045       0   235.5      .1       0
Bank Sta=196.2,235.5
XS Rating Curve= 0 ,0
Exp/Cntr=0.3,0.1

Type RM Length L Ch R = 1 ,37964   ,293.3,304,314.6
XS GIS Cut Line= 2
     1952163.876      373877.786      1952224.64      374320.494
#Sta/Elev= 30
       0 2272.25     9.7  2266.9    19.4 2261.16    38.9 2249.14    48.6 2243.29
    58.3 2237.86      68 2234.07    77.7 2231.79    87.4 2229.89    97.1 2227.78
   106.9  2224.9   116.6 2221.26   126.3 2218.43     136 2217.29   165.1 2217.07
   184.6 2216.38   194.3 2215.85     204 2215.06   213.7 2214.18   223.4 2214.23
   242.9 2215.72   291.4 2217.51   320.6 2218.38   330.3 2218.76     340 2219.34
   349.7 2220.16   359.4 2221.23   398.3 2225.94   427.4 2229.69   446.9 2231.99
#Mann= 3 , 0 , 0
       0      .1       0     204    .045       0   242.9      .1       0
Bank Sta=204,242.9
XS Rating Curve= 0 ,0
Exp/Cntr=0.3,0.1

Type RM Length L Ch R = 1 ,37660.1 ,477.6,491.9,506.2
XS GIS Cut Line= 2
     1951968.564      373882.126     1951825.335      374303.133
#Sta/Elev= 30
       0 2264.17     9.7 2259.59    19.3 2254.44    67.7 2225.55    77.3 2221.23
      87  2219.2     116 2216.09   125.7 2214.53   154.7 2208.68   164.4    2207
     174  2205.7   183.7 2205.01   193.4 2204.75     203 2203.99   212.7 2201.96
   224.2 2198.74     232 2196.96   241.7 2196.48   251.4 2197.26     261 2197.99
     290 2198.84     319 2200.13   328.7 2200.62   338.4 2201.47     348 2203.49
   357.7 2207.07   415.7 2231.74   425.4 2234.78     435 2236.27   444.7 2237.34
#Mann= 3 , 0 , 0
       0      .1       0   224.2    .045       0   251.4      .1       0
Bank Sta=224.2,251.4
XS Rating Curve= 0 ,0
Exp/Cntr=0.3,0.1

Type RM Length L Ch R = 1 ,37168.2 ,465.5,450,434.4
XS GIS Cut Line= 2
     1951621.342      373738.897     1951408.668      373899.487
#Sta/Elev= 25
       0 2229.44     9.5 2225.28      19  2220.2    28.6 2212.85    38.1 2204.08
    47.6 2195.01    57.1 2187.18    66.6 2183.74    85.7  2183.6    95.2 2181.75
   100.12180.058   104.7 2178.47   114.2 2176.94   123.7 2178.08   133.2 2179.57
   142.8 2180.59   152.3 2180.82   171.3 2180.86   180.8 2181.25   190.4 2182.21
   199.9 2183.28   209.4 2184.48   218.9 2185.79   228.4  2187.2   266.5 2193.24
#Mann= 3 , 0 , 0
       0      .1       0   100.1    .045       0   123.7      .1       0
Bank Sta=100.1,123.7
XS Rating Curve= 0 ,0
Exp/Cntr=0.3,0.1

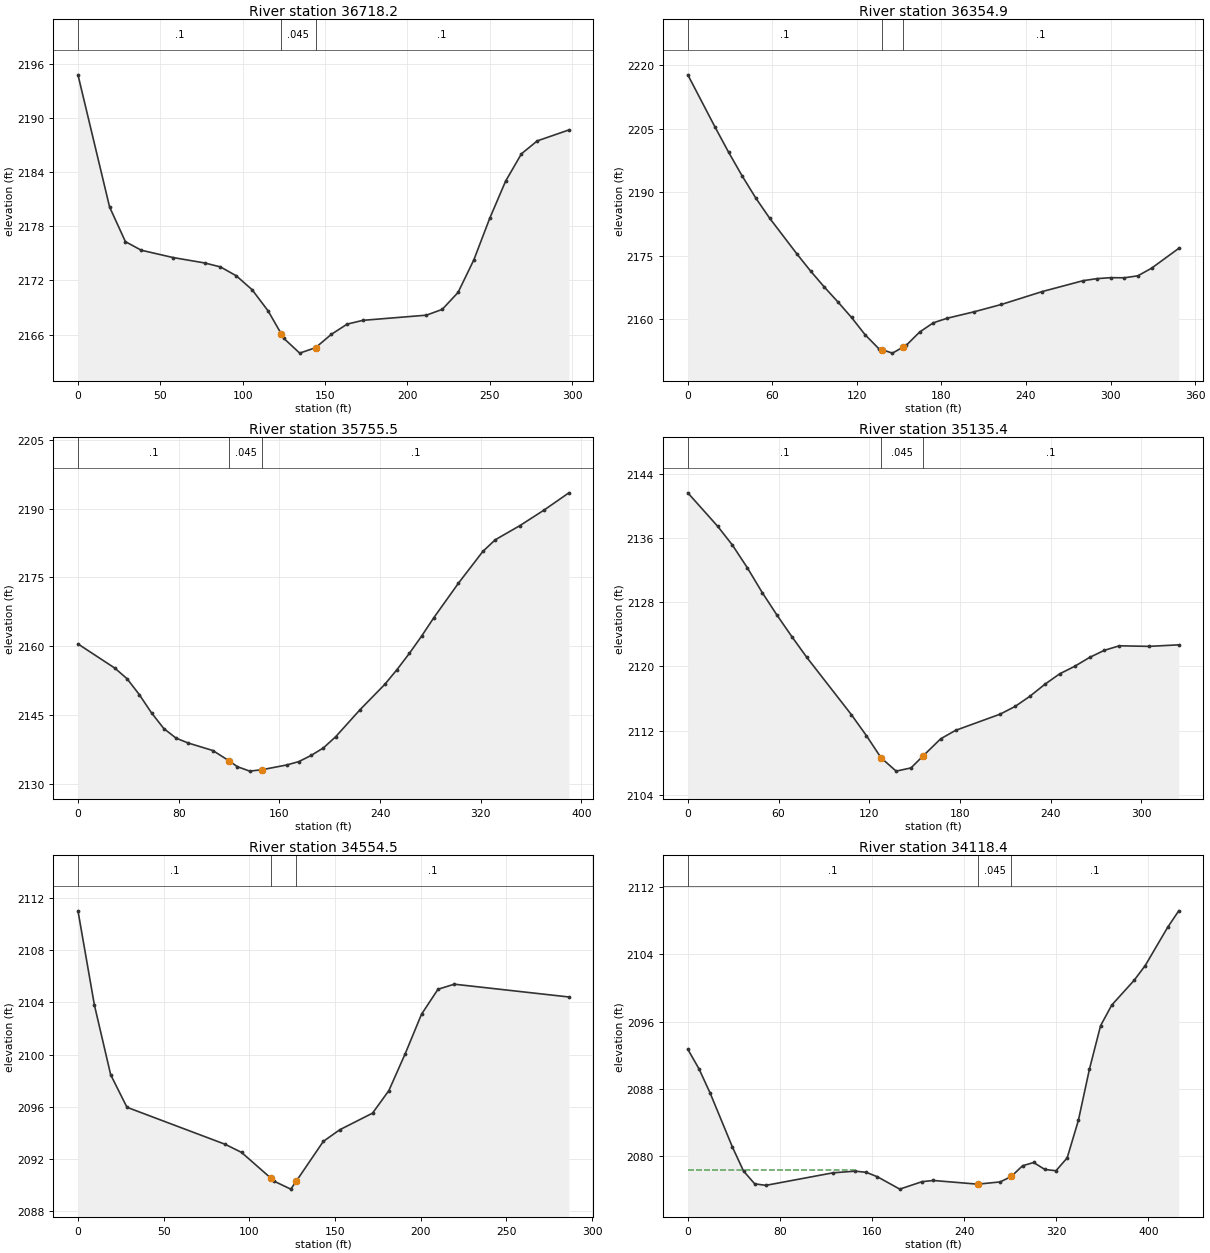
Type RM Length L Ch R = 1 ,36718.2 ,373.6,363.3,351.4
XS GIS Cut Line= 2
     1951178.633      373556.605     1951113.529      373847.404
#Sta/Elev= 26
       0 2194.76    19.2 2180.13    28.8  2176.3    38.4 2175.35    57.7 2174.54
    76.9 2173.94    86.5  2173.5    96.1 2172.52   105.7 2170.98   115.4 2168.64
   123.3 2166.13     125 2165.59   134.6 2163.96   144.2 2164.56   153.8 2166.04
   163.4 2167.17     173 2167.59   211.5 2168.16   221.1  2168.8   230.7 2170.67
   240.3 2174.28   249.9 2178.86   259.6    2183   269.2 2186.02   278.8 2187.45
     298 2188.66
#Mann= 3 , 0 , 0
       0      .1       0   123.3    .045       0   144.2      .1       0
Bank Sta=123.3,144.2
XS Rating Curve= 0 ,0
Exp/Cntr=0.3,0.1

Type RM Length L Ch R = 1 ,36354.9 ,587.1,599.3,611.6
XS GIS Cut Line= 2
     1950801.029      373526.224     1950883.494      373864.765
#Sta/Elev= 30
       0 2217.75    19.4 2205.34      29 2199.41    38.7 2193.76    48.4 2188.52
    58.1 2183.83    77.4  2175.4    87.1 2171.35    96.8 2167.58   106.5 2164.04
   116.2 2160.35   125.8 2156.28   135.5 2152.99   137.9 2152.73   145.2 2151.92
   152.9 2153.36   154.9 2153.73   164.5  2156.9   174.2 2159.09   183.9 2160.16
   203.3 2161.71   222.6 2163.44   251.6 2166.49   280.7 2169.07   290.4 2169.54
     300 2169.77   309.7 2169.74   319.4 2170.21   329.1 2172.01   348.4  2176.7
#Mann= 3 , 0 , 0
       0      .1       0   137.9    .045       0   152.9      .1       0
Bank Sta=137.9,152.9
XS Rating Curve= 0 ,0
Exp/Cntr=0.3,0.1

Type RM Length L Ch R = 1 ,35755.5 ,611.5,620.1,628.5
XS GIS Cut Line= 2
     1950358.321      373560.946     1950245.474       373934.21
#Sta/Elev= 30
       0 2160.53    29.2 2155.28      39 2152.96    48.7 2149.51    58.5  2145.5
    68.2 2142.11      78 2140.01    87.7 2138.95   107.2 2137.32   120.1 2135.07
   126.7  2133.8   136.5 2132.84   146.2 2133.15   165.7 2134.17   175.5 2134.92
   185.2 2136.25     195  2137.9   204.7 2140.32   224.2 2146.25   243.7 2151.71
   253.5 2154.96   263.2 2158.45     273 2162.23   282.7 2166.24   302.2 2173.73
   321.7 2180.68   331.5  2183.2     351 2186.27   370.4 2189.69     390 2193.42
#Mann= 3 , 0 , 0
       0      .1       0   120.1    .045       0   146.2      .1       0
Bank Sta=120.1,146.2
XS Rating Curve= 0 ,0
Exp/Cntr=0.3,0.1

Type RM Length L Ch R = 1 ,35135.4 ,596.2,580.9,565.4
XS GIS Cut Line= 2
     1949889.571      373287.508     1949689.918      373543.585
#Sta/Elev= 27
       0  2141.6    19.7 2137.45    29.5  2135.1    39.4 2132.27    49.2  2129.2
      59 2126.38    68.9 2123.69    78.7 2121.13   108.2    2114   118.1  2111.4
   127.9 2108.62   137.8 2106.98   147.6 2107.38   155.7 2108.89   167.3 2111.01
   177.1 2112.05   206.6 2114.07   216.5 2115.03   226.3  2116.3   236.2 2117.79
     246 2119.09   255.8 2120.01   265.7 2121.12   275.5 2122.01   285.4 2122.57
     305  2122.5   324.7 2122.69
#Mann= 3 , 0 , 0
       0      .1       0   127.9    .045       0   155.7      .1       0
Bank Sta=127.9,155.7
XS Rating Curve= 0 ,0
Exp/Cntr=0.3,0.1

Type RM Length L Ch R = 1 ,34554.5 ,456.9,436.2,415.4
XS GIS Cut Line= 2
     1949260.231       373309.21     1949264.571      373595.668
#Sta/Elev= 19
       0 2111.01     9.6 2103.79    19.1 2098.45    28.6 2095.96      86 2093.12
    95.5  2092.5   112.5 2090.54   114.6 2090.29   124.2 2089.69   127.5 2090.32
   143.2 2093.35   152.8 2094.24   171.9 2095.51   181.4 2097.23     191 2100.07
   200.5 2103.09   210.1    2105   219.6 2105.39   286.5 2104.41
#Mann= 3 , 0 , 0
       0      .1       0   112.5    .045       0   127.5      .1       0
Bank Sta=112.5,127.5
XS Rating Curve= 0 ,0
Exp/Cntr=0.3,0.1

Type RM Length L Ch R = 1 ,34118.4 ,313.1,329.3,346.3
XS GIS Cut Line= 2
     1948726.376       373474.14     1949060.578      373738.897
#Sta/Elev= 30
       0  2092.7     9.7 2090.37    19.4 2087.48    38.8 2081.04    48.4  2078.2
    58.1 2076.68    67.8  2076.5     126 2077.99   145.4 2078.19     155 2078.05
   164.7 2077.52   184.1 2076.05   203.5 2076.94   213.2 2077.08   251.9 2076.64
   271.3 2076.91     281 2077.56   290.7 2078.83   300.4 2079.22   310.1 2078.39
   319.8 2078.24   329.5 2079.77   339.2 2084.22   348.8 2090.31   358.5  2095.5
   368.2 2097.96   387.6  2100.9   397.3 2102.67   416.7  2107.2   426.4 2109.18
#Mann= 3 , 0 , 0
       0      .1       0   251.9    .045       0     281      .1       0
#XS Ineff= 2 , 0
          145.07 2078.38
Permanent Ineff=
       F       F
Bank Sta=251.9,281
XS Rating Curve= 0 ,0
Exp/Cntr=0.3,0.1

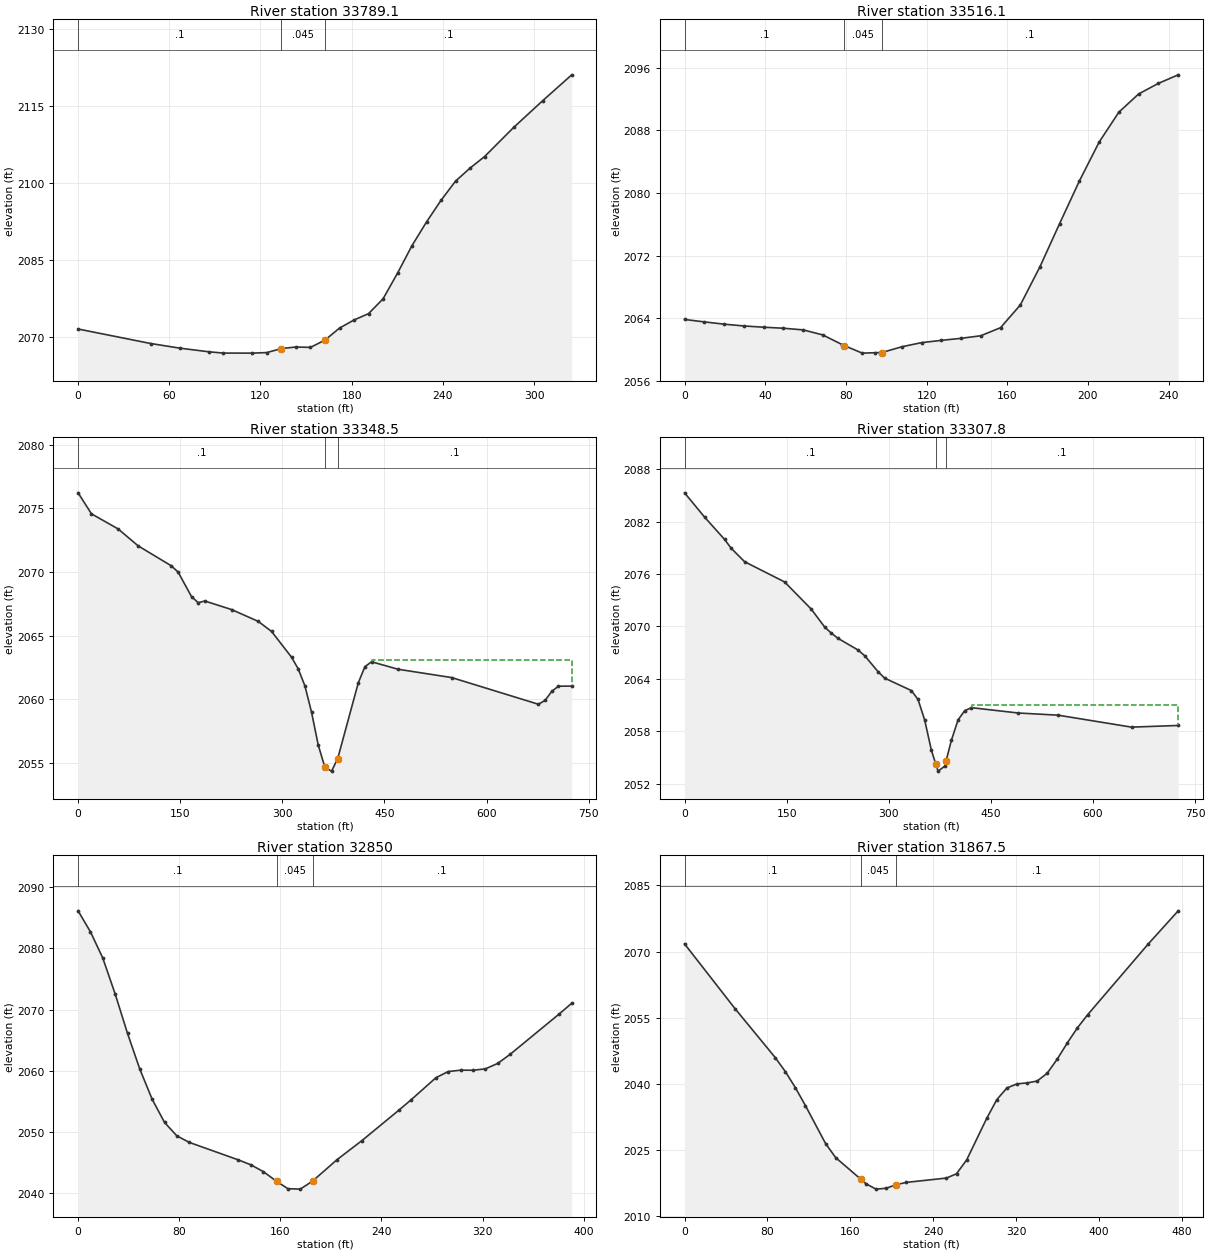
Type RM Length L Ch R = 1 ,33789.1 ,268.9,273,276.3
XS GIS Cut Line= 2
     1948640.933      373592.817     1948689.544      373913.998
#Sta/Elev= 25
       0 2071.55    47.8 2068.73    66.9 2067.83      86 2067.12    95.5 2066.87
   114.6 2066.86   124.2 2066.97   133.8 2067.75   143.3 2068.05   152.9 2067.98
   162.4 2069.39     172 2071.73   181.5  2073.3   191.1 2074.54   200.6  2077.4
   210.2 2082.43   219.7 2087.78   229.3  2092.4   238.8 2096.59   248.4 2100.34
     258 2102.88   267.5 2105.11   286.6 2110.77   305.7 2115.97   324.8    2121
#Mann= 3 , 0 , 0
       0      .1       0   133.8    .045       0   162.4      .1       0
Bank Sta=133.8,162.4
XS Rating Curve= 0 ,0
Exp/Cntr=0.3,0.1

Type RM Length L Ch R = 1 ,33516.1 ,142,167.6,193
XS GIS Cut Line= 2
     1948406.064      373674.661     1948404.328      373919.453
#Sta/Elev= 28
       0 2063.85     9.8 2063.54    19.6 2063.25    29.4 2063.02    39.2 2062.86
      49 2062.73    58.8 2062.52    68.5 2061.88    78.3 2060.62    79.2 2060.52
    88.1 2059.55    94.2  2059.6    97.9 2059.63   107.7 2060.36   117.5 2060.89
   127.3 2061.18   137.1 2061.44   146.9 2061.77   156.7  2062.8   166.5  2065.7
   176.2 2070.56     186  2076.1   195.8 2081.54   205.6 2086.51   215.4 2090.34
   225.2 2092.66     235 2094.01   244.8  2095.1
#Mann= 3 , 0 , 0
       0      .1       0    79.2    .045       0    97.9      .1       0
Bank Sta=79.2,97.9
XS Rating Curve= 0 ,0
Exp/Cntr=0.3,0.1

Type RM Length L Ch R = 1 ,33348.5 ,41.3,40.7,40.1
XS GIS Cut Line= 2
     1948596.689      373521.768     1947949.119      373848.156
#Sta/Elev= 30
       0 2076.23    19.6 2074.58    58.8 2073.39    88.2 2072.06   137.2 2070.48
     147 2069.99   166.6 2068.07   176.4 2067.59   186.2 2067.72   225.4 2067.05
   264.6 2066.12   284.2 2065.33   313.6  2063.3   323.4 2062.38   333.2 2061.05
     343 2058.96   352.8 2056.39   362.6 2054.63   372.4 2054.34   381.4 2055.33
   411.6 2061.28   421.4 2062.56   431.2 2062.94   470.4 2062.35   548.8  2061.7
   676.2  2059.6     686  2059.9   695.8 2060.61   705.6 2061.02   725.2 2061.03
#Mann= 3 , 0 , 0
       0      .1       0   362.6    .045       0   381.4      .1       0
#XS Ineff= 2 , 0
                          431.55         2063.12
Permanent Ineff=
       F       F
Bank Sta=362.6,381.4
XS Rating Curve= 0 ,0
Exp/Cntr=0.3,0.1

Type RM Length L Ch R = 1 ,33307.8 ,490.2,457.8,425
XS GIS Cut Line= 2
     1948572.383      373490.518     1947924.814      373816.906
#Sta/Elev= 30
       0  2085.3    29.4 2082.52    58.8 2079.96    68.6 2078.94    88.2 2077.41
     147 2075.09   186.2 2071.97   205.8 2069.93   215.6 2069.23   225.4 2068.63
   254.8  2067.3   264.6 2066.64   284.2 2064.82     294 2064.07   333.2 2062.65
     343 2061.63   352.8 2059.26   362.6 2055.81   369.3 2054.18   372.4 2053.42
   382.2 2053.98   384.3 2054.62     392 2056.95   401.8 2059.29   411.6 2060.35
   421.4 2060.69     490 2060.08   548.8 2059.83   656.6 2058.46   725.2 2058.65
#Mann= 3 , 0 , 0
       0      .1       0   369.3    .045       0   384.3      .1       0
#XS Ineff= 2 , 0
                          422.54         2060.98
Permanent Ineff=
       F       F
Bank Sta=369.3,384.3
XS Rating Curve= 0 ,0
Exp/Cntr=0.3,0.1

Type RM Length L Ch R = 1 ,32850   ,984,982.5,980.8
XS GIS Cut Line= 2
     1947762.922      373591.646     1947862.748       373969.25
#Sta/Elev= 30
       0 2086.12     9.8 2082.68    19.5 2078.42    29.3 2072.56    39.1  2066.1
    48.8 2060.28    58.6 2055.34    68.4 2051.56    78.1 2049.37    87.9  2048.3
   126.9 2045.43   136.7 2044.63   146.5 2043.53   157.2 2041.92     166 2040.73
   175.8 2040.66   185.5 2041.97     205 2045.49   224.6 2048.59   253.9 2053.57
   263.6 2055.27   283.2 2058.87   292.9 2059.87   302.7 2060.09   312.5 2060.08
   322.2  2060.3     332 2061.19   341.8 2062.67   380.8 2069.29   390.6 2071.03
#Mann= 3 , 0 , 0
       0      .1       0   157.2    .045       0   185.5      .1       0
Bank Sta=157.2,185.5
XS Rating Curve= 0 ,0
Exp/Cntr=0.3,0.1

Type RM Length L Ch R = 1 ,31867.5 ,1030.1,1036.7,1042.5
XS GIS Cut Line= 2
     1946825.422      373826.021     1946977.331       374277.41
#Sta/Elev= 30
       0 2071.75    48.6 2057.11    87.5    2046    97.2 2042.84   106.9 2039.19
   116.6 2035.13   136.1 2026.51   145.8 2023.34     170 2018.46     175 2017.43
   184.7  2016.2   194.4 2016.39   204.1 2017.19   213.8 2017.72   252.7 2018.71
   262.4 2019.68   272.2 2022.82   291.6 2032.26   301.3 2036.48     311 2039.11
   320.8 2040.04   330.5 2040.26   340.2 2040.68   349.9 2042.45   359.6 2045.65
   369.4 2049.35   379.1 2052.75   388.8 2055.67   447.1 2071.65   476.3 2079.24
#Mann= 3 , 0 , 0
       0      .1       0     170    .045       0   204.1      .1       0
Bank Sta=170,204.1
XS Rating Curve= 0 ,0
Exp/Cntr=0.3,0.1

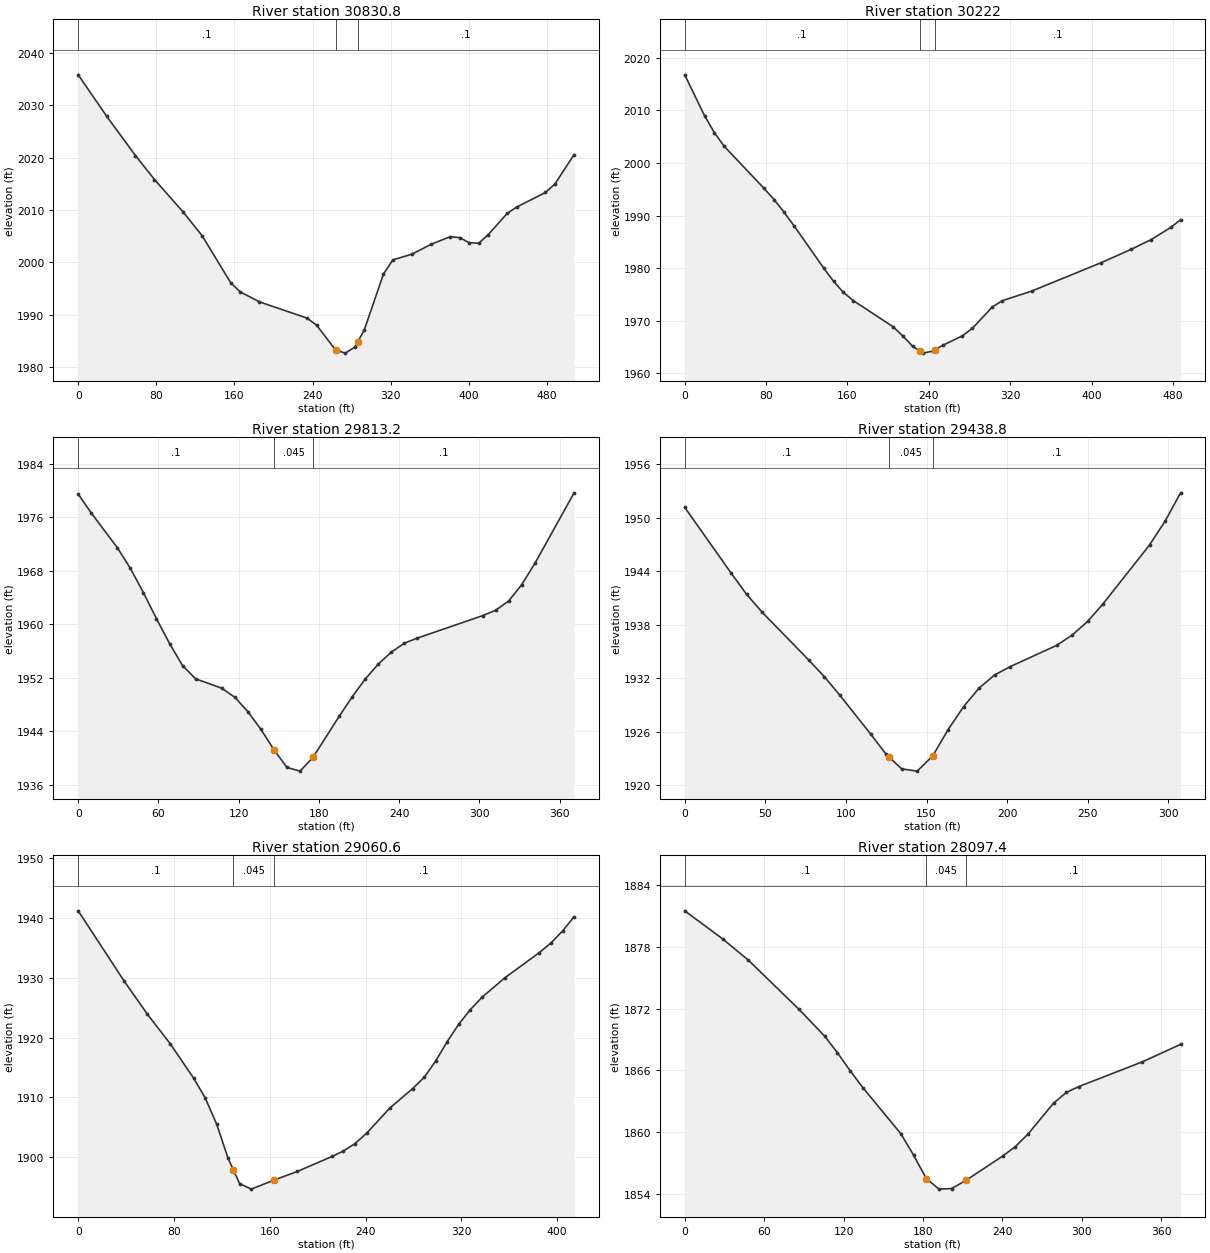
Type RM Length L Ch R = 1 ,30830.8 ,622.2,608.8,595.2
XS GIS Cut Line= 2
     1945935.665      373986.611     1945944.345      374494.424
#Sta/Elev= 30
       0 2035.79    29.3 2027.85    58.6  2020.4    78.1 2015.82   107.4 2009.64
     127 2005.07   156.3  1996.1     166 1994.38   185.6 1992.48   234.4 1989.38
   244.2 1988.02   263.7 1983.29   273.5  1982.7   283.2 1983.82   286.2 1984.83
     293 1987.12   312.6 1997.76   322.3  2000.5   341.8 2001.57   361.4 2003.46
   380.9 2004.91   390.7 2004.74   400.4 2003.77   410.2 2003.66     420 2005.31
   439.5 2009.38   449.3 2010.59   478.6 2013.35   488.4    2015   507.9 2020.58
#Mann= 3 , 0 , 0
       0      .1       0   263.7    .045       0   286.2      .1       0
Bank Sta=263.7,286.2
XS Rating Curve= 0 ,0
Exp/Cntr=0.3,0.1

Type RM Length L Ch R = 1 ,30222   ,420.2,408.8,397.4
XS GIS Cut Line= 2
      1945245.56      374247.028     1945518.998      374650.674
#Sta/Elev= 30
       0 2016.74    19.5 2008.96    29.2 2005.72      39 2003.12      78 1995.15
    87.8 1993.04    97.5 1990.66   107.3 1988.08   136.5 1980.04   146.3 1977.49
     156 1975.38   165.8 1973.81   204.8 1968.86   214.5 1967.08   224.3  1965.1
     231 1964.23     234 1963.84   243.8 1964.22     246 1964.47   253.5 1965.31
     273 1967.13   282.8 1968.56   302.3  1972.6     312 1973.79   341.3 1975.65
   409.5 1981.04   438.8 1983.56   458.3  1985.4   477.8 1987.72   487.5 1989.21
#Mann= 3 , 0 , 0
       0      .1       0     231    .045       0     246      .1       0
Bank Sta=231,246
XS Rating Curve= 0 ,0
Exp/Cntr=0.3,0.1

Type RM Length L Ch R = 1 ,29813.2 ,372.4,374.4,376.4
XS GIS Cut Line= 2
     1945041.567      374720.118     1945371.428      374889.389
#Sta/Elev= 30
       0 1979.43     9.8 1976.61    29.3 1971.42      39 1968.35    48.8  1964.7
    58.5 1960.83    68.3 1957.11      78 1953.82    87.8 1951.83   107.3 1950.44
   117.1 1949.07   126.8 1946.95   136.6 1944.29   146.4 1941.23   156.1 1938.59
   165.9 1938.04   175.6 1940.11   195.1 1946.22   204.9 1949.15   214.6  1951.8
   224.4 1954.04   234.2 1955.83   243.9 1957.16   253.7 1957.93   302.5 1961.28
   312.2 1962.08     322 1963.49   331.7 1965.93   341.5 1969.09   370.8 1979.63
#Mann= 3 , 0 , 0
       0      .1       0   146.4    .045       0   175.6      .1       0
Bank Sta=146.4,175.6
XS Rating Curve= 0 ,0
Exp/Cntr=0.3,0.1

Type RM Length L Ch R = 1 ,29438.8 ,368,378.3,388.8
XS GIS Cut Line= 2
     1944893.905      375029.388     1945152.151      375196.489
#Sta/Elev= 25
       0 1951.14    28.8 1943.77    38.4 1941.39    48.1 1939.38    76.9 1934.04
    86.5 1932.19    96.1 1930.12   115.4 1925.73     125 1923.46     127 1923.12
   134.6 1921.84   144.2 1921.59   153.8 1923.29   163.4 1926.25     173 1928.82
   182.6  1930.9   192.2 1932.36   201.9  1933.3   230.7 1935.68   240.3 1936.83
   249.9 1938.36   259.5 1940.34   288.4 1946.95     298 1949.61   307.6 1952.77
#Mann= 3 , 0 , 0
       0      .1       0     127    .045       0   153.8      .1       0
Bank Sta=127,153.8
XS Rating Curve= 0 ,0
Exp/Cntr=0.3,0.1

Type RM Length L Ch R = 1 ,29060.6 ,944.3,963.1,980.8
XS GIS Cut Line= 2
     1944655.283      375180.188     1944880.977       375527.41
#Sta/Elev= 30
       0 1941.17    38.5  1929.4    57.8  1923.9      77 1918.93    96.3 1913.25
   105.9 1909.99   115.6 1905.56   125.2 1899.83   129.5 1897.94   134.8 1895.62
   144.5  1894.7   163.7 1896.22     183 1897.65   211.9 1900.15   221.5 1901.07
   231.1  1902.3   240.8 1904.02     260  1908.2   279.3 1911.49   288.9 1913.36
   298.6 1916.12   308.2 1919.35   317.8 1922.24   327.4 1924.66   337.1 1926.71
   356.3 1929.99   385.2 1934.21   394.9 1935.83   404.5 1937.81   414.1 1940.18
#Mann= 3 , 0 , 0
       0      .1       0   129.5    .045       0   163.7      .1       0
Bank Sta=129.5,163.7
XS Rating Curve= 0 ,0
Exp/Cntr=0.3,0.1

Type RM Length L Ch R = 1 ,28097.4 ,423.6,396.3,368.8
XS GIS Cut Line= 2
     1943947.817      375427.583     1943882.713      375796.507
#Sta/Elev= 22
       0 1881.48    28.8 1878.74      48  1876.7    86.4 1871.91   105.7 1869.32
   115.3 1867.72   124.9 1865.97   134.5 1864.33   163.3 1859.84   172.9 1857.76
   182.5 1855.49   192.1 1854.47   201.7 1854.53   212.8 1855.35   240.1 1857.67
   249.8  1858.6   259.4 1859.83   278.6 1862.81   288.2 1863.85   297.8 1864.43
   345.8 1866.83   374.6 1868.52
#Mann= 3 , 0 , 0
       0      .1       0   182.5    .045       0   212.8      .1       0
Bank Sta=182.5,212.8
XS Rating Curve= 0 ,0
Exp/Cntr=0.3,0.1

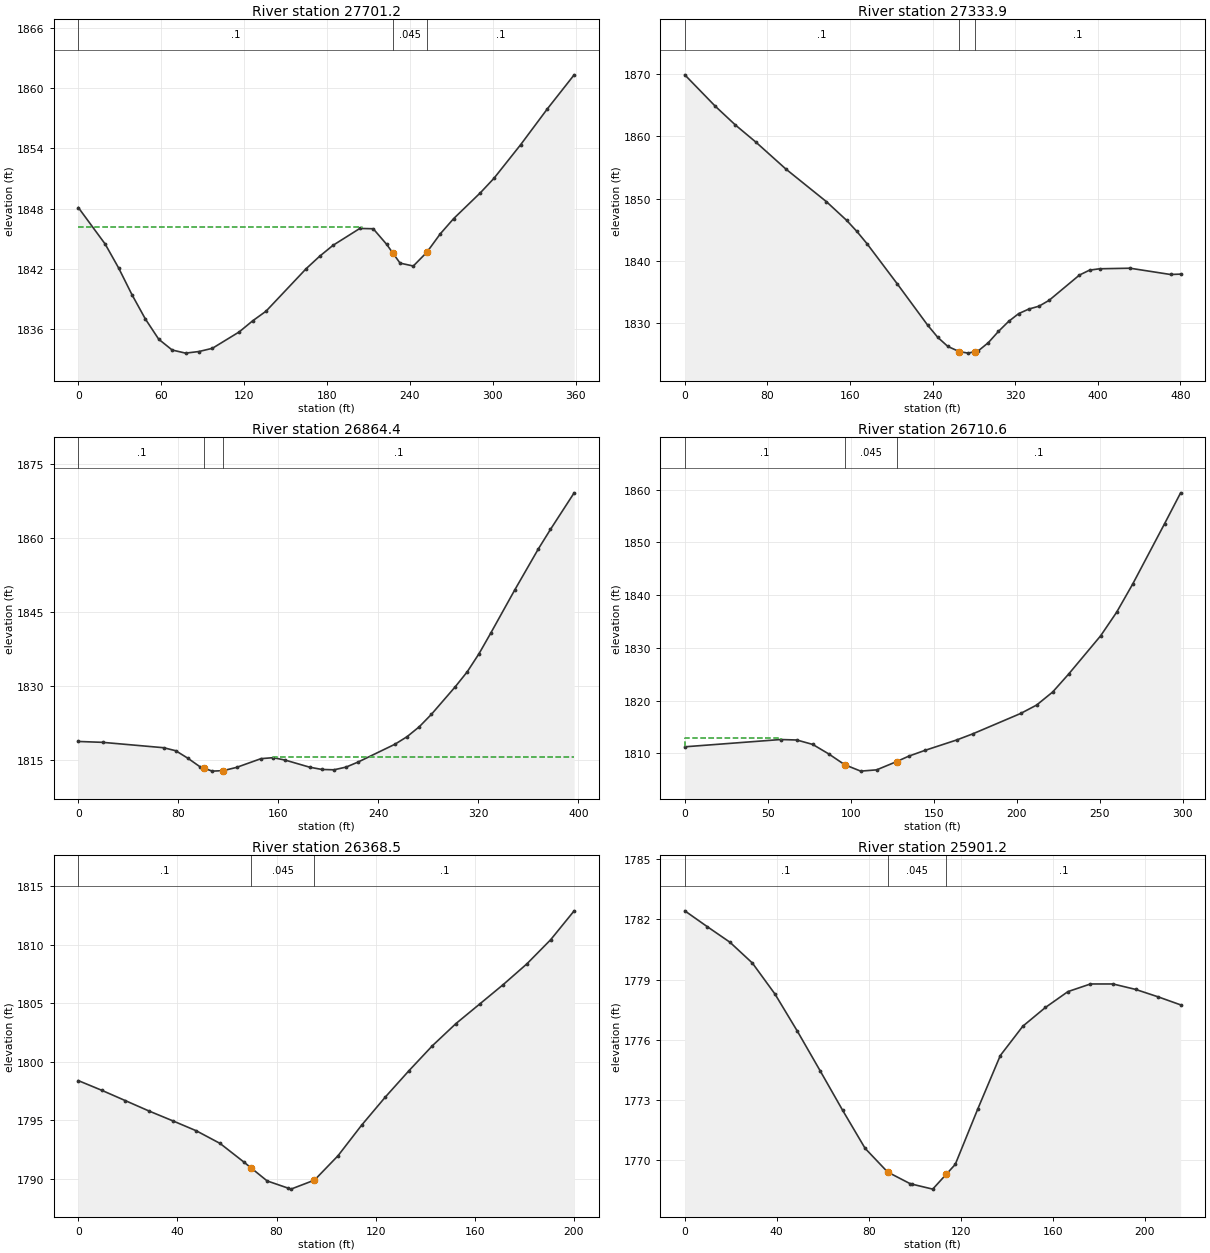
Type RM Length L Ch R = 1 ,27701.2 ,363.8,367.3,370.7
XS GIS Cut Line= 2
     1943461.706      375714.042     1943765.526      375905.014
#Sta/Elev= 30
       0  1848.1    19.4 1844.47    29.1  1842.1    38.8 1839.43    48.5 1837.01
    58.2 1834.99    67.9 1833.92    77.6 1833.61    87.3 1833.77      97 1834.09
   116.4 1835.72   126.1 1836.82   135.8 1837.78   164.9 1842.02   174.6 1843.25
   184.3 1844.34   203.7 1846.02   213.4 1845.99   223.1 1844.44   227.4 1843.61
   232.8 1842.57   242.4 1842.28   252.2 1843.65   261.9 1845.48   271.6    1847
     291 1849.58   300.7    1851   320.1 1854.36   339.5 1857.94   358.8 1861.31
#Mann= 3 , 0 , 0
       0      .1       0   227.4    .045       0   252.2      .1       0
#XS Ineff= 2 , 0
          205.07 1846.17
Permanent Ineff=
       F       F
Bank Sta=227.4,252.2
XS Rating Curve= 0 ,0
Exp/Cntr=0.3,0.1

Type RM Length L Ch R = 1 ,27333.9 ,484.5,469.5,454.6
XS GIS Cut Line= 2
     1943166.567      375887.653     1943531.151      376200.153
#Sta/Elev= 30
       0 1869.92    29.4 1864.89      49 1861.85    68.6 1859.13      98 1854.75
   137.2 1849.51   156.8  1846.5   166.6 1844.74   176.4 1842.77   205.8 1836.29
   235.2 1829.65     245 1827.69   254.8 1826.22   265.8  1825.4   274.4 1825.15
   280.8 1825.39   284.2 1825.51     294 1826.84   303.8 1828.65   313.6 1830.25
   323.4 1831.51   333.2 1832.24     343  1832.7   352.8 1833.64   382.2 1837.71
     392  1838.5   401.8 1838.72   431.2 1838.81   470.4  1837.8   480.2 1837.86
#Mann= 3 , 0 , 0
       0      .1       0   265.8    .045       0   280.8      .1       0
Bank Sta=265.8,280.8
XS Rating Curve= 0 ,0
Exp/Cntr=0.3,0.1

Type RM Length L Ch R = 1 ,26864.4 ,150.6,153.7,156.9
XS GIS Cut Line= 3
     1943127.505       376473.59     1943409.623      376486.611
      1943522.47      376503.972
#Sta/Elev= 30
       0 1818.77    19.5 1818.59    68.2  1817.5    77.9 1816.89    87.6 1815.37
    97.4 1813.62   100.9 1813.31   107.1 1812.75   115.9 1812.85   126.6 1813.51
   146.1 1815.28   155.8 1815.48   165.6 1814.98     185 1813.55   194.8 1813.09
   204.5 1813.02   214.2 1813.57     224 1814.62   253.2  1818.2   262.9 1819.73
   272.7 1821.75   282.4 1824.27   301.4 1829.84     311 1832.88   320.5 1836.58
     330 1840.81     349 1849.48     368 1857.86   377.6 1861.78   396.6 1869.22
#Mann= 3 , 0 , 0
       0      .1       0   100.9    .045       0   115.9      .1       0
#XS Ineff= 2 , 0
                          156.06         1815.71
Permanent Ineff=
       F       F
Bank Sta=100.9,115.9
XS Rating Curve= 0 ,0
Exp/Cntr=0.3,0.1

Type RM Length L Ch R = 1 ,26710.6 ,320.4,342.2,364
XS GIS Cut Line= 2
     1943131.752      376604.909     1943424.721      376663.502
#Sta/Elev= 22
       0 1811.25    57.8 1812.63    67.5 1812.54    77.1  1811.7    86.7 1809.91
    96.4 1807.85     106 1806.64   115.6 1806.88   127.6 1808.44   134.9 1809.47
   144.6 1810.56   163.8 1812.54   173.5  1813.7   202.4 1817.57     212 1819.16
   221.7 1821.64   231.3 1825.03   250.6 1832.29   260.2 1836.74   269.9 1842.09
   289.1 1853.52   298.8 1859.39
#Mann= 3 , 0 , 0
       0      .1       0    96.4    .045       0   127.6      .1       0
#XS Ineff= 2 , 0
           57.89 1812.99
Permanent Ineff=
       F       F
Bank Sta=96.4,127.6
XS Rating Curve= 0 ,0
Exp/Cntr=0.3,0.1

Type RM Length L Ch R = 1 ,26368.5 ,472.6,467.2,461.7
XS GIS Cut Line= 2
     1943010.317      376816.472     1943092.783      376998.764
#Sta/Elev= 24
       0  1798.4     9.5 1797.57      19 1796.69    28.6  1795.8    38.1 1794.97
    47.6 1794.12    57.2 1793.04    66.7 1791.47    69.6 1790.97    76.2 1789.84
    84.6 1789.23    85.8 1789.14    95.3 1789.91   104.8 1791.99   114.3 1794.59
   123.9    1797   133.4 1799.24   142.9 1801.38   152.4 1803.27     162 1804.94
   171.5  1806.6     181 1808.36   190.6 1810.42   200.1 1812.89
#Mann= 3 , 0 , 0
       0      .1       0    69.6    .045       0    95.3      .1       0
Bank Sta=69.6,95.3
XS Rating Curve= 0 ,0
Exp/Cntr=0.3,0.1

Type RM Length L Ch R = 1 ,25901.2 ,441.2,431.4,421.6
XS GIS Cut Line= 2
     1942558.928      376977.063     1942697.817      377141.993
#Sta/Elev= 25
       0 1782.42     9.8 1781.63    19.6 1780.86    29.4 1779.82    39.2 1778.28
      49 1776.42    58.8 1774.47    68.6  1772.5    78.4  1770.6    88.2 1769.42
      98 1768.84    98.7 1768.82   107.8 1768.57   113.7 1769.31   117.6  1769.8
   127.4 1772.56   137.2 1775.22     147 1776.68   156.8 1777.61   166.6  1778.4
   176.4 1778.78   186.2 1778.78     196 1778.51   205.8 1778.14   215.6 1777.74
#Mann= 3 , 0 , 0
       0      .1       0    88.2    .045       0   113.7      .1       0
Bank Sta=88.2,113.7
XS Rating Curve= 0 ,0
Exp/Cntr=0.3,0.1

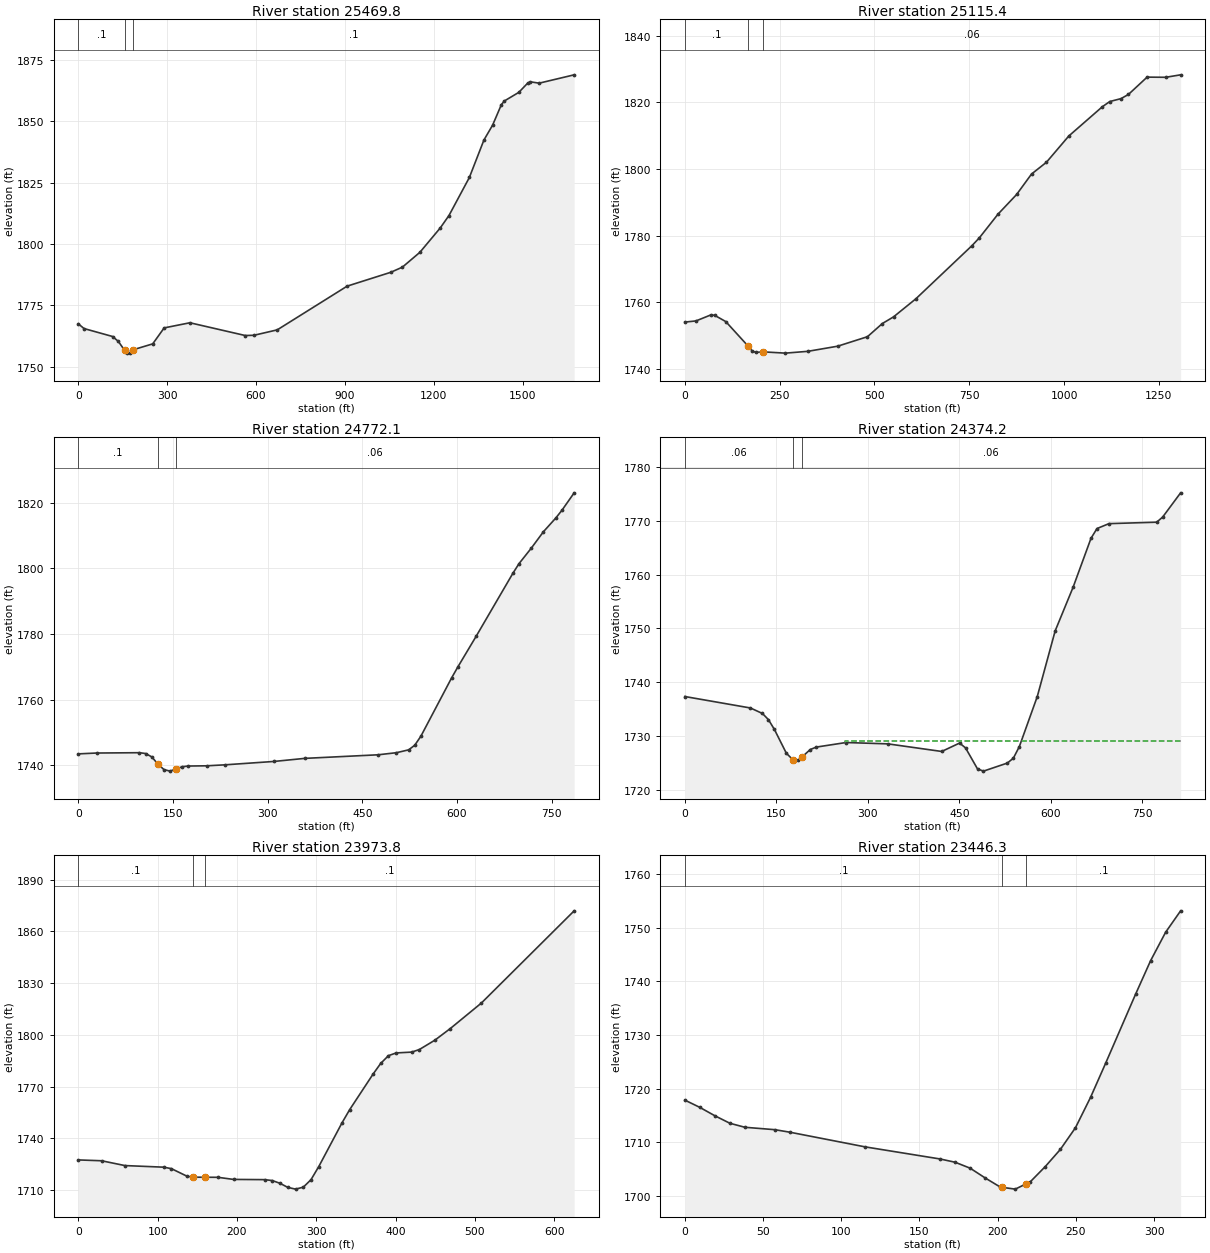
Type RM Length L Ch R = 1 ,25469.8 ,346.1,354.5,362.6
XS GIS Cut Line= 3
     1942168.303      377276.542     1942511.185      377432.792
     1943617.956      378109.875
#Sta/Elev= 30
       0  1767.5    19.3 1765.57   115.9 1762.33   135.3 1760.31   155.9 1756.77
   164.2 1755.57   173.9 1755.58   183.6 1756.89   251.2 1759.34   289.8 1765.84
   376.8 1767.93   563.6 1762.74     593 1762.83   671.7 1765.04   907.6 1782.83
    1055 1788.47  1094.3 1790.57  1153.3  1796.6  1222.1 1806.52  1251.6 1811.59
  1320.4 1827.06  1369.6 1842.31    1399 1848.39  1428.5  1856.7  1438.4 1858.19
  1487.5 1861.72    1517 1865.43  1526.8 1865.99  1556.3 1865.46  1674.3 1868.85
#Mann= 3 , 0 , 0
       0      .1       0   155.9    .045       0   183.6      .1       0
Bank Sta=155.9,183.6
XS Rating Curve= 0 ,0
Exp/Cntr=0.3,0.1

Type RM Length L Ch R = 1 ,25115.4 ,342.9,343.3,343.6
XS GIS Cut Line= 2
     1941942.609      377454.493     1942880.109      378365.952
#Sta/Elev= 30
       0 1754.02    29.5 1754.37    68.8 1756.18    78.6 1756.06   108.1 1754.17
   166.8 1746.83     177 1745.45   186.8 1744.91   206.4 1745.08   265.4  1744.7
   324.4 1745.24   403.1 1746.78   481.7 1749.63     521 1753.59   550.5 1755.59
   609.5 1761.03     757 1776.94   776.7 1779.31   825.8 1786.41     875 1792.33
   914.3 1798.47   953.6    1802  1012.6 1809.89  1101.1 1818.68  1120.8 1820.25
  1150.2 1821.11  1169.9 1822.37  1219.1 1827.57  1268.2 1827.52  1307.5 1828.26
#Mann= 3 , 0 , 0
       0      .1       0   166.8    .045       0   206.4     .06       0
Bank Sta=166.8,206.4
XS Rating Curve= 0 ,0
Exp/Cntr=0.3,0.1

Type RM Length L Ch R = 1 ,24772.1 ,366.8,397.9,428.5
XS GIS Cut Line= 3
     1941768.998      377749.632     1942163.963      378135.917
      1942276.81       378339.91
#Sta/Elev= 30
       0 1743.52    29.1 1743.78    96.9 1743.88   106.6 1743.63   116.3 1742.61
     126 1740.45   135.7 1738.73   145.4 1738.27   155.1 1738.97   164.8 1739.61
   174.5 1739.82   203.5 1739.89   232.6 1740.19   310.2 1741.22   358.6 1742.15
   474.9 1743.24     504 1743.88   523.4 1744.75   533.1 1746.17   542.8 1748.92
   591.3  1766.6     601 1769.88   630.2 1779.28   688.4 1798.45   698.2 1801.42
   717.6 1806.12     737 1811.16   756.4 1815.29   766.2 1817.66   785.6 1822.98
#Mann= 3 , 0 , 0
       0      .1       0     126    .045       0   155.1     .06       0
Bank Sta=126,155.1
XS Rating Curve= 0 ,0
Exp/Cntr=0.3,0.1

Type RM Length L Ch R = 1 ,24374.2 ,386.4,400.4,414.7
XS GIS Cut Line= 2
     1941582.366      377649.806      1941174.38      378352.931
#Sta/Elev= 30
       0 1737.37   107.7 1735.24   127.3 1734.22   137.1 1733.08   146.9 1731.26
   166.5 1726.84     177 1725.66   186.1 1725.55     192 1726.13   205.7 1727.53
   215.5 1727.98   264.4 1728.83     333 1728.58   421.2 1727.17   450.5 1728.73
   460.3 1727.83   479.9 1723.93   489.7 1723.52   528.9 1725.02   538.7 1725.93
   548.5 1728.08   577.9 1737.37   607.2 1749.55   636.6 1757.65     666 1766.75
   675.8 1768.55   695.4 1769.46   773.7 1769.73   783.5 1770.69   812.9 1775.18
#Mann= 3 , 0 , 0
       0     .06       0     177    .045       0     192     .06       0
#XS Ineff= 2 , 0
                          261.97          1729.1
Permanent Ineff=
       F       F
Bank Sta=177,192
XS Rating Curve= 0 ,0
Exp/Cntr=0.3,0.1

Type RM Length L Ch R = 1 ,23973.8 ,517.4,527.5,536.9
XS GIS Cut Line= 3
     1941304.588      377493.556     1941039.831      377641.125
     1940718.651      377662.827
#Sta/Elev= 30
       0 1727.45    29.3 1726.97    58.7 1724.18   107.6 1723.25   117.3  1722.4
   136.9 1718.02   144.4 1717.45   159.4 1717.41     176 1717.37   195.6 1716.15
   234.7 1716.02   244.4  1715.5   254.2  1713.9     264 1711.53   273.8 1710.52
   283.6 1711.66   293.3 1716.01   303.1 1723.62   332.4 1748.98   342.1 1756.66
   371.4 1777.14   381.2 1783.45   390.9  1787.9   400.6 1789.49   420.2 1789.97
   429.9 1791.47   449.4 1796.88   468.9 1803.64     508  1818.4     625 1871.89
#Mann= 3 , 0 , 0
       0      .1       0   144.4    .045       0   159.4      .1       0
Bank Sta=144.4,159.4
XS Rating Curve= 0 ,0
Exp/Cntr=0.3,0.1

Type RM Length L Ch R = 1 ,23446.3 ,486.7,482.7,478.5
XS GIS Cut Line= 2
     1941235.144      377120.292     1940918.303      377124.632
#Sta/Elev= 26
       0 1717.88     9.6 1716.52    19.2 1714.96    28.8 1713.56    38.4 1712.81
    57.6 1712.36    67.2 1711.89   115.2 1709.16   163.2  1706.9   172.8 1706.29
   182.4 1705.18     192 1703.36   201.6 1701.67     203 1701.61   211.2 1701.28
     218 1702.24   220.8 1702.64   230.4 1705.49     240 1708.67   249.7 1712.73
   259.3 1718.37   268.9  1724.7   288.1 1737.61   297.7 1743.86   307.3 1749.16
   316.9 1753.16
#Mann= 3 , 0 , 0
       0      .1       0     203    .045       0     218      .1       0
Bank Sta=203,218
XS Rating Curve= 0 ,0
Exp/Cntr=0.3,0.1