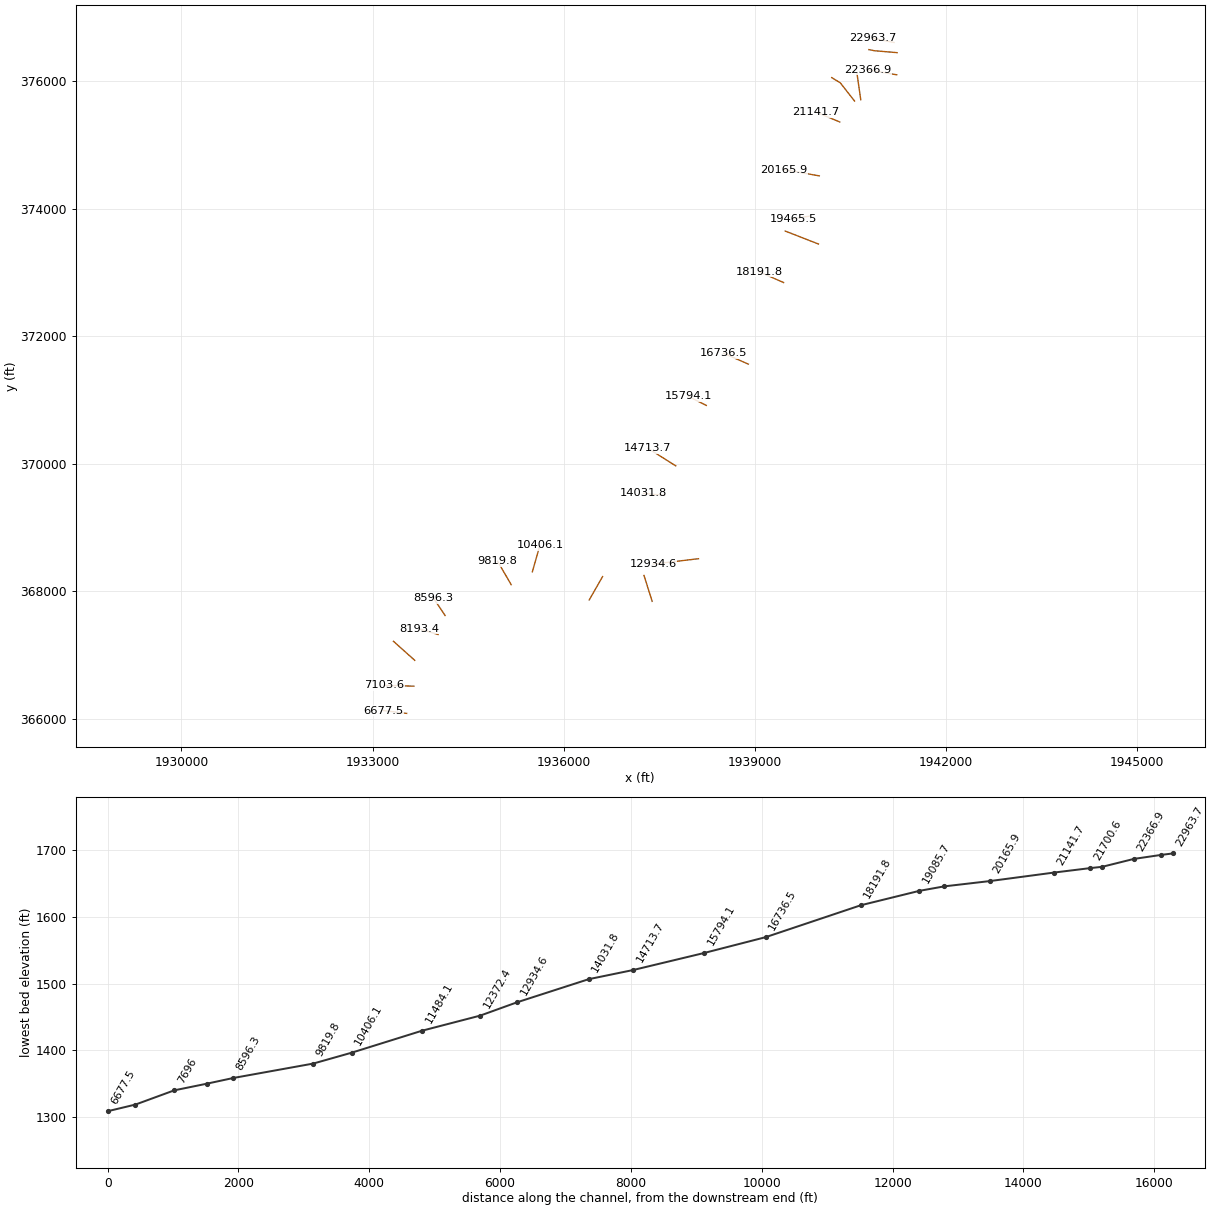
HEC-RAS study ROARINGCK.prj: ROARINGCK

--- ROARINGCK.g01 (geometry) --- (continued)

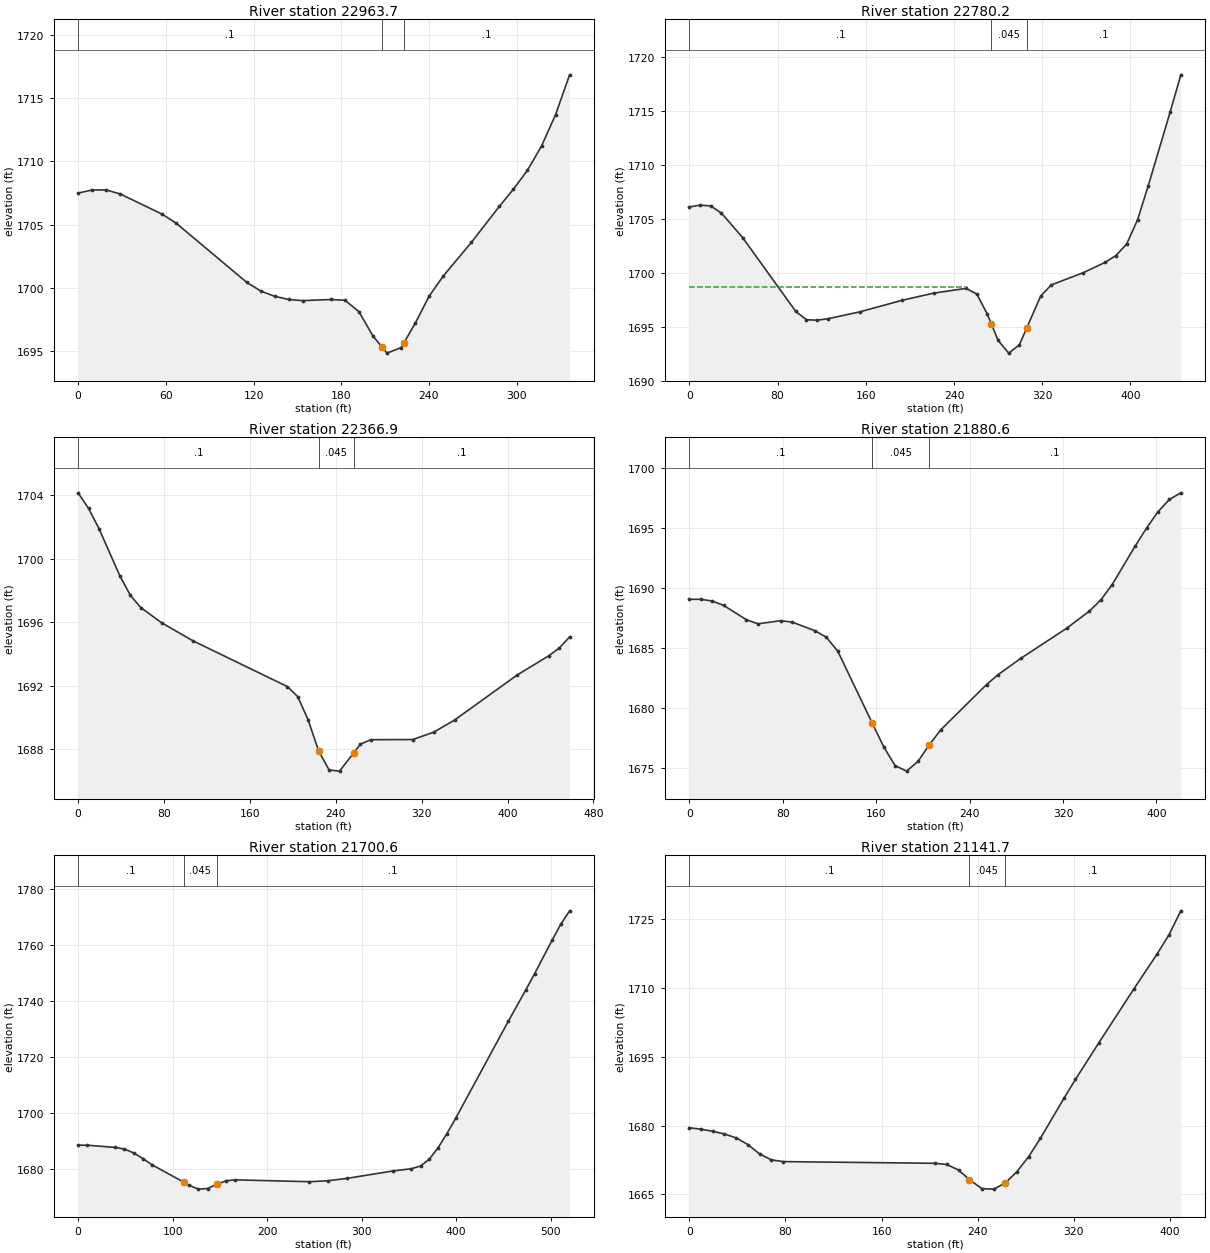
Type RM Length L Ch R = 1 ,22963.7 ,181.2,183.4,185.6
XS GIS Cut Line= 2
      1941183.06      376603.799     1940853.199      376668.903
#Sta/Elev= 29
       0 1707.49     9.6 1707.74    19.2 1707.74    28.8 1707.42    57.6 1705.82
    67.2  1705.1   115.3 1700.44   124.9 1699.75   134.5 1699.33   144.1 1699.08
   153.7 1698.99   172.9 1699.08   182.5 1699.02   192.1 1698.12   201.7 1696.19
   207.7 1695.35   211.3 1694.84     221 1695.28   222.7 1695.62   230.6  1697.2
   240.2 1699.36   249.8 1700.94     269 1703.59   288.2 1706.45   297.8  1707.8
   307.4  1709.3     317 1711.21   326.6 1713.69   336.2 1716.84
#Mann= 3 , 0 , 0
       0      .1       0   207.7    .045       0   222.7      .1       0
Bank Sta=207.7,222.7
XS Rating Curve= 0 ,0
Exp/Cntr=0.3,0.1

Type RM Length L Ch R = 1 ,22780.2 ,416.2,413.4,409.3
XS GIS Cut Line= 3
      1941230.71      376444.318     1940874.808        376474.7
     1940788.002      376492.061
#Sta/Elev= 30
       0 1706.12     9.6 1706.29    19.3 1706.22      29 1705.56    48.3 1703.28
    96.5 1696.42   106.2 1695.65   115.8 1695.61   125.5 1695.74   154.5 1696.38
   193.1 1697.46     222 1698.13     251 1698.56   260.7 1698.03   270.3 1696.15
  273.941695.242     280 1693.73   289.6 1692.55   299.3 1693.32   305.9 1694.88
   318.6 1697.85   328.2 1698.88   357.2 1700.02   376.9 1700.97   386.7  1701.6
   396.5 1702.67   406.4 1704.91   416.2 1708.11   435.9  1714.9   445.7 1718.39
#Mann= 3 , 0 , 0
       0      .1       0  273.94    .045       0   305.9      .1       0
#XS Ineff= 2 , 0
           250.7 1698.69
Permanent Ineff=
       F       F
Bank Sta=273.94,305.9
XS Rating Curve= 0 ,0
Exp/Cntr=0.3,0.1

Type RM Length L Ch R = 1 ,22366.9 ,514.7,486.2,457.5
XS GIS Cut Line= 2
      1941226.37      376097.096     1940775.074      376174.111
#Sta/Elev= 24
       0 1704.14     9.7 1703.16    19.5 1701.88      39 1698.89    48.7 1697.68
    58.4 1696.91    77.9 1695.95   107.2 1694.81   194.8 1691.94   204.6  1691.3
   214.3 1689.83     224 1687.89   233.8 1686.68   243.5 1686.61   256.7 1687.76
     263 1688.31   272.7 1688.59   311.7  1688.6   331.2 1689.06   350.7 1689.83
   409.1 1692.67   438.3 1693.87   448.1 1694.36   457.8 1695.06
#Mann= 3 , 0 , 0
       0      .1       0     224    .045       0   256.7      .1       0
Bank Sta=224,256.7
XS Rating Curve= 0 ,0
Exp/Cntr=0.3,0.1

Type RM Length L Ch R = 1 ,21880.6 ,167.4,180,192.8
XS GIS Cut Line= 2
     1940661.706      375705.491     1940601.463      376122.028
#Sta/Elev= 30
       0 1689.07     9.8 1689.07    19.6 1688.93    29.4 1688.56    48.9 1687.37
    58.7 1687.03    78.3 1687.29    88.1 1687.17   107.7 1686.45   117.4 1685.91
   127.2 1684.73   156.6 1678.76   166.4 1676.79   176.2 1675.22     186 1674.76
   195.8 1675.57   205.5 1676.96   215.3  1678.2   254.5 1681.97   264.3 1682.79
   283.8 1684.15     323 1686.65   342.6 1688.09   352.4 1689.02   362.1  1690.3
   381.7 1693.49   391.5    1695   401.3 1696.36   411.1 1697.39   420.9 1697.94
#Mann= 3 , 0 , 0
       0      .1       0   156.6    .045       0   205.5      .1       0
Bank Sta=156.6,205.5
XS Rating Curve= 0 ,0
Exp/Cntr=0.3,0.1

Type RM Length L Ch R = 1 ,21700.6 ,547.1,559,570.2
XS GIS Cut Line= 3
     1940564.478       375684.77     1940341.047      375970.118
     1940206.498      376052.583
#Sta/Elev= 30
       0 1688.54     9.8 1688.52    39.2 1687.75      49 1687.16    58.8 1685.78
    68.6 1683.77    78.4 1681.51   111.6  1675.4   117.5 1674.22   127.3 1672.87
   137.1 1673.09   146.9 1674.62   156.7 1675.87   166.5 1676.17   244.9 1675.52
   264.5 1675.85   284.1 1676.68     333 1679.33   352.6 1680.14   362.4 1681.12
   371.7 1683.55     381 1687.59   390.3 1692.64   399.6  1698.1   455.2 1732.63
   473.8 1743.85   483.1 1749.62   501.7 1761.61   510.9  1767.3   520.2 1772.08
#Mann= 3 , 0 , 0
       0      .1       0   111.6    .045       0   146.9      .1       0
Bank Sta=111.6,146.9
XS Rating Curve= 0 ,0
Exp/Cntr=0.3,0.1

Type RM Length L Ch R = 1 ,21141.7 ,970.1,975.8,981.1
XS GIS Cut Line= 2
     1940332.273      375357.079     1939954.762      375514.389
#Sta/Elev= 26
       0 1679.52     9.7  1679.2    19.5 1678.75    29.2 1678.16      39  1677.3
    48.7 1675.86    58.4 1673.81    68.2 1672.52    77.9 1672.13   204.5 1671.76
   214.2  1671.5     224 1670.29   233.1 1668.19   243.4 1666.23   253.2 1666.12
   262.9 1667.44   272.6 1669.94   282.4 1673.23   292.1  1677.2   311.6 1685.91
   321.3 1690.08   340.8 1698.09     370 1709.87   389.5 1717.57   399.2 1721.69
     409 1726.89
#Mann= 3 , 0 , 0
       0      .1       0   233.1    .045       0   262.9      .1       0
Bank Sta=233.1,262.9
XS Rating Curve= 0 ,0
Exp/Cntr=0.3,0.1

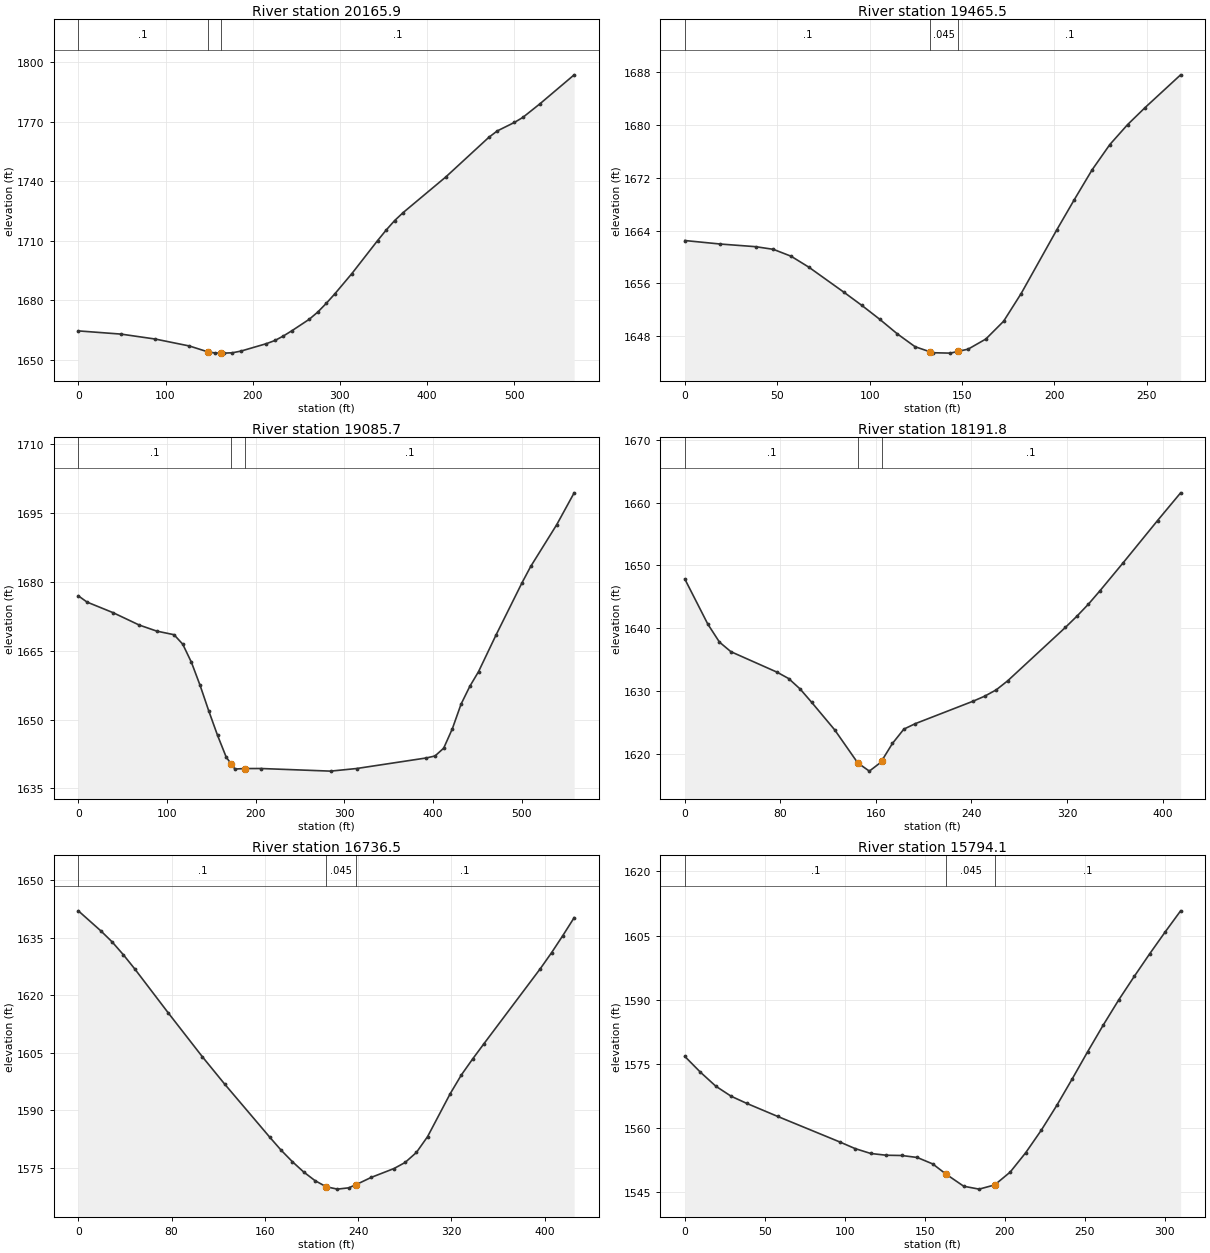
Type RM Length L Ch R = 1 ,20165.9 ,692.4,700.4,708
XS GIS Cut Line= 2
     1940011.185      374511.785      1939451.29      374611.611
#Sta/Elev= 30
       0 1664.66      49 1663.04    88.2 1660.55   127.5 1657.04   148.9 1654.04
   156.9 1653.53   163.9 1653.47   166.7 1653.45   176.5 1653.62   186.3 1654.45
   215.7 1658.22   225.5 1659.82   235.3 1662.12   245.1 1664.78   264.8  1670.5
   274.6 1674.14   284.4 1678.56   294.2 1683.34   313.8 1693.58   343.2 1710.16
     353 1715.45   362.8 1720.28   372.6 1724.32   421.6 1742.31   470.7 1762.19
   480.5 1765.47   500.1 1769.73   509.9  1772.3   529.5 1779.16   568.7 1793.75
#Mann= 3 , 0 , 0
       0      .1       0   148.9    .045       0   163.9      .1       0
Bank Sta=148.9,163.9
XS Rating Curve= 0 ,0
Exp/Cntr=0.3,0.1

Type RM Length L Ch R = 1 ,19465.5 ,392,379.9,367.4
XS GIS Cut Line= 2
     1939867.956      373882.445     1939603.199      373839.042
#Sta/Elev= 26
       0 1662.49    19.2 1661.96    38.3 1661.56    47.9 1661.16    57.5 1660.12
    67.1 1658.47    86.2 1654.66    95.8 1652.69   105.4 1650.61     115 1648.39
   124.6 1646.45   132.8 1645.67   134.2 1645.54   143.7 1645.48   147.8 1645.74
   153.3 1646.08   162.9 1647.61   172.5 1650.29     182 1654.48   201.2 1664.06
   210.8 1668.68   220.4 1673.17     230 1676.99   239.6    1680   249.1 1682.58
   268.3 1687.52
#Mann= 3 , 0 , 0
       0      .1       0   132.8    .045       0   147.8      .1       0
Bank Sta=132.8,147.8
XS Rating Curve= 0 ,0
Exp/Cntr=0.3,0.1

Type RM Length L Ch R = 1 ,19085.7 ,895.3,893.9,892.4
XS GIS Cut Line= 2
     1939997.731      373442.919     1939476.897      373646.044
#Sta/Elev= 30
       0 1676.96     9.8  1675.6    39.2 1673.29    68.6  1670.6    88.3 1669.28
   107.9 1668.49   117.7 1666.43   127.5 1662.48   137.3 1657.44   147.1 1651.86
   156.9 1646.59   166.7 1641.83   172.5 1640.29   176.5 1639.23   187.5 1639.33
     206 1639.34   284.4 1638.77   313.8 1639.34   392.3 1641.64   402.1 1642.07
   411.9 1643.77   421.7 1648.02   431.5 1653.37   441.4 1657.26   451.2 1660.45
   470.8 1668.38   500.2  1679.8     510 1683.36   539.4 1692.48     559  1699.4
#Mann= 3 , 0 , 0
       0      .1       0   172.5    .045       0   187.5      .1       0
Bank Sta=172.5,187.5
XS Rating Curve= 0 ,0
Exp/Cntr=0.3,0.1

Type RM Length L Ch R = 1 ,18191.8 ,1455.6,1455.3,1454.8
XS GIS Cut Line= 2
     1939450.856      372838.752     1939070.647      373005.419
#Sta/Elev= 27
       0 1647.84    19.3 1640.64      29 1637.79    38.6 1636.26    77.2    1633
    86.9 1631.99    96.5 1630.33   106.2  1628.2   125.5 1623.81   144.8 1618.55
   154.5 1617.24   164.1 1618.64   164.7 1618.83   173.8 1621.64   183.4 1623.93
   193.1 1624.81   241.4 1628.38     251 1629.17   260.7 1630.18   270.3 1631.62
   318.6 1640.12   328.2  1641.9   337.9 1643.83   347.6 1645.97   366.9  1650.4
   395.8 1657.15   415.1 1661.56
#Mann= 3 , 0 , 0
       0      .1       0   144.8    .045       0   164.7      .1       0
Bank Sta=144.8,164.7
XS Rating Curve= 0 ,0
Exp/Cntr=0.3,0.1

Type RM Length L Ch R = 1 ,16736.5 ,943.7,942.3,940.4
XS GIS Cut Line= 2
     1938897.811      371559.336     1938508.147      371729.377
#Sta/Elev= 30
       0 1641.98    19.3 1636.76      29 1633.88    38.6 1630.54    48.3 1626.88
    77.3 1615.31   106.3 1603.98   125.6 1596.79   164.3 1582.94   173.9 1579.61
   183.6  1576.6   193.2 1573.94   202.9 1571.69   212.6 1570.07   222.2 1569.46
   231.9  1569.8   238.4 1570.66   251.2 1572.52   270.6 1574.81   280.2  1576.4
   289.9 1579.01   299.5 1583.14   318.9 1594.33   328.5 1599.23   338.2  1603.4
   347.8 1607.34   396.2 1626.92   405.8 1631.06   415.5 1635.54   425.2  1640.2
#Mann= 3 , 0 , 0
       0      .1       0   212.6    .045       0   238.4      .1       0
Bank Sta=212.6,238.4
XS Rating Curve= 0 ,0
Exp/Cntr=0.3,0.1

Type RM Length L Ch R = 1 ,15794.1 ,1083.6,1080.4,1076.7
XS GIS Cut Line= 2
     1938237.314      370911.669     1937961.272      371052.294
#Sta/Elev= 29
       0 1576.76     9.7 1573.09    19.4 1569.79      29 1567.44    38.7 1565.78
    58.1 1562.72    96.8 1556.77   106.5  1555.2   116.2 1554.07   125.9 1553.66
   135.5  1553.6   145.2 1553.14   154.9 1551.63   163.5 1549.17   174.3 1546.41
   183.9 1545.74   193.6 1546.72   203.3 1549.72     213 1554.25   222.7 1559.49
   232.4 1565.29     242 1571.46   251.7 1577.85   261.4 1584.05   271.1 1589.95
   280.8 1595.44   290.4  1600.7   300.1 1605.82   309.8 1610.78
#Mann= 3 , 0 , 0
       0      .1       0   163.5    .045       0   193.6      .1       0
Bank Sta=163.5,193.6
XS Rating Curve= 0 ,0
Exp/Cntr=0.3,0.1

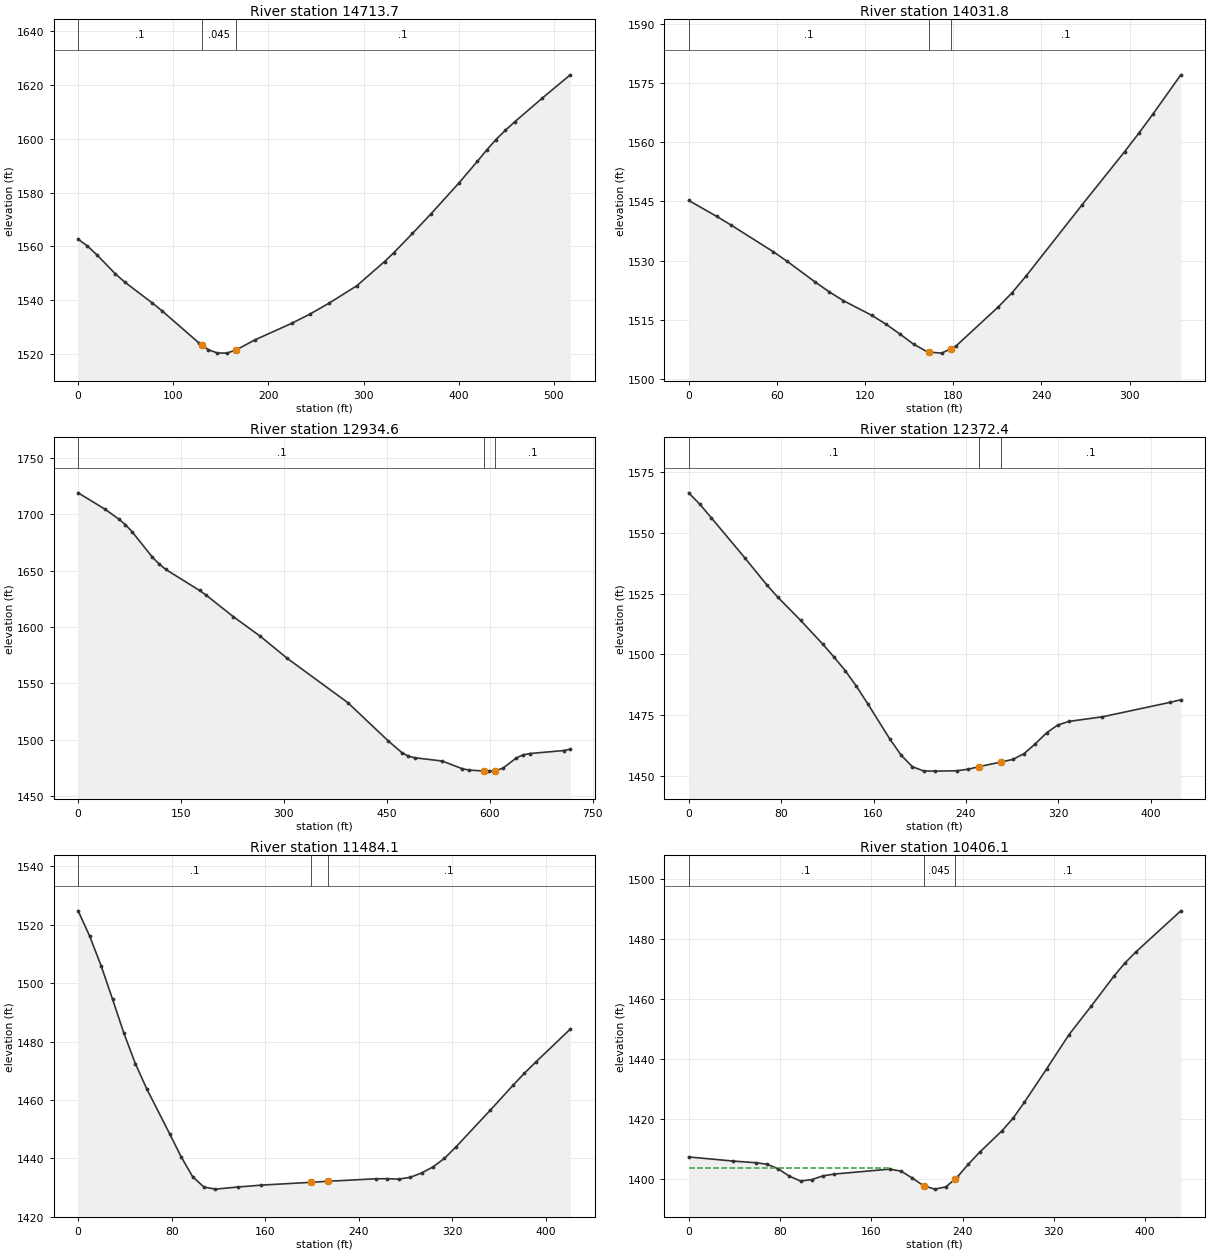
Type RM Length L Ch R = 1 ,14713.7 ,672.1,681.9,691.7
XS GIS Cut Line= 2
     1937758.147      369963.752     1937320.647      370239.794
#Sta/Elev= 30
       0 1562.66     9.8 1560.13    19.5 1556.94      39 1549.85    48.8  1546.8
    78.1 1538.93    87.8 1536.17   126.9 1524.16   129.8 1523.42   136.6 1521.67
   146.4 1520.39   156.2 1520.35   165.9 1521.51   185.4  1525.2   224.5 1531.43
     244 1534.92   263.5 1538.86   292.8 1545.34   322.1 1554.37   331.9 1557.69
   351.4  1564.8   370.9 1572.09   400.2 1583.53   419.7 1591.62   429.5 1595.82
   439.2 1599.69     449  1603.1   458.7 1606.21     488 1615.12   517.3 1623.73
#Mann= 3 , 0 , 0
       0      .1       0   129.8    .045       0   165.9      .1       0
Bank Sta=129.8,165.9
XS Rating Curve= 0 ,0
Exp/Cntr=0.3,0.1

Type RM Length L Ch R = 1 ,14031.8 ,1092.2,1097.2,1101.8
XS GIS Cut Line= 2
     1937586.272      369500.211     1937252.939      369531.461
#Sta/Elev= 25
       0 1545.24    19.1 1541.18    28.7 1539.03    57.4 1532.29      67 1529.82
    86.1 1524.57    95.7 1522.08   105.2 1519.88   124.4 1516.18   133.9    1514
   143.5 1511.48     153 1508.85   162.6 1506.87   163.4 1506.85   172.2 1506.59
   178.4 1507.74   181.8 1508.37   210.4  1518.2     220 1521.87   229.6 1526.13
   267.8  1544.2   296.5 1557.54   306.1 1562.18   315.7 1567.01   334.8 1577.02
#Mann= 3 , 0 , 0
       0      .1       0   163.4    .045       0   178.4      .1       0
Bank Sta=163.4,178.4
XS Rating Curve= 0 ,0
Exp/Cntr=0.3,0.1

Type RM Length L Ch R = 1 ,12934.6 ,593.7,562.1,530.4
XS GIS Cut Line= 2
     1938114.806      368507.581     1937402.468      368422.991
#Sta/Elev= 30
       0 1719.14    39.3 1704.53      59 1695.94    68.8  1690.9    78.6 1684.62
   108.1 1662.09   117.9    1656   127.8 1651.06   176.9 1632.44   186.7 1628.21
     226 1609.22   265.3 1591.82   304.6  1572.2   393.1 1532.74     452 1498.78
   471.7 1488.42   481.5 1485.17   491.3 1483.75   530.6 1480.89   560.1 1474.03
   569.9 1472.84   592.2 1472.02   599.4 1471.93   607.2 1472.21   619.1  1474.5
   638.7 1483.68   648.6  1486.4   658.4 1487.56   707.5  1490.2   717.3  1491.4
#Mann= 3 , 0 , 0
       0      .1       0   592.2    .045       0   607.2      .1       0
Bank Sta=592.2,607.2
XS Rating Curve= 0 ,0
Exp/Cntr=0.3,0.1

Type RM Length L Ch R = 1 ,12372.4 ,907.2,888.3,869.3
XS GIS Cut Line= 2
     1937388.356      367838.752        1937260.      368244.907
#Sta/Elev= 30
       0 1566.38     9.7 1561.66    19.4 1556.24    48.4 1539.78    67.8 1528.45
    77.4 1523.38    96.8 1514.03   116.2 1504.16   125.8 1498.92   135.5 1493.34
   145.2 1486.92   154.9 1479.82   174.2 1465.18   183.9 1458.62   193.6 1453.88
   203.3 1452.13     213 1452.05   232.3  1452.2     242 1452.85   251.7 1453.93
   270.3 1455.78   280.7 1456.88   290.4 1459.28   300.1 1463.29   309.8 1467.79
   319.5    1471   329.2 1472.48   358.2 1474.37   416.3 1480.26     426 1481.38
#Mann= 3 , 0 , 0
       0      .1       0   251.7    .045       0   270.3      .1       0
Bank Sta=251.7,270.3
XS Rating Curve= 0 ,0
Exp/Cntr=0.3,0.1

Type RM Length L Ch R = 1 ,11484.1 ,1072.6,1078,1083.4
XS GIS Cut Line= 2
     1936400.743      367862.025     1936609.992      368227.098
#Sta/Elev= 29
       0 1524.76     9.8 1516.14    19.6 1506.01    29.4 1494.52    39.1 1482.88
    48.9 1472.46    58.7 1463.77    78.3 1448.38    88.1 1440.54    97.9 1433.72
   107.6 1430.17   117.4 1429.47     137 1430.21   156.6 1430.84   198.8  1431.8
   213.8 1432.16   254.4 1433.01   264.2 1433.04     274 1432.89   283.8  1433.5
   293.6 1434.98   303.4 1437.07   313.2    1440   322.9 1443.86   352.3 1456.45
   371.9 1465.05   381.6 1469.16   391.4 1473.02   420.8 1484.26
#Mann= 3 , 0 , 0
       0      .1       0   198.8    .045       0   213.8      .1       0
Bank Sta=198.8,213.8
XS Rating Curve= 0 ,0
Exp/Cntr=0.3,0.1

Type RM Length L Ch R = 1 ,10406.1 ,567.8,586.2,604.4
XS GIS Cut Line= 2
     1935508.054      368301.957     1935626.075      368716.831
#Sta/Elev= 30
       0 1407.24    39.2 1405.86    58.8 1405.32    68.6 1404.82    78.4  1403.3
    88.2 1400.85      98 1399.23   107.8 1399.68   117.6 1400.93   127.4 1401.54
   176.4 1403.19   186.3 1402.48   196.1 1400.18   205.9 1397.65   215.7 1396.52
   225.5 1397.28   233.6 1399.95   235.3 1400.51   245.1 1404.82   254.9 1408.78
   274.5 1415.92   284.3 1420.15   294.1 1425.41   313.7 1436.59   333.3 1447.99
   352.9 1457.55   372.5 1467.38   382.3 1471.85   392.1 1475.61   431.3 1489.24
#Mann= 3 , 0 , 0
       0      .1       0   205.9    .045       0   233.6      .1       0
#XS Ineff= 2 , 0
          176.76 1403.67
Permanent Ineff=
       F       F
Bank Sta=205.9,233.6
XS Rating Curve= 0 ,0
Exp/Cntr=0.3,0.1

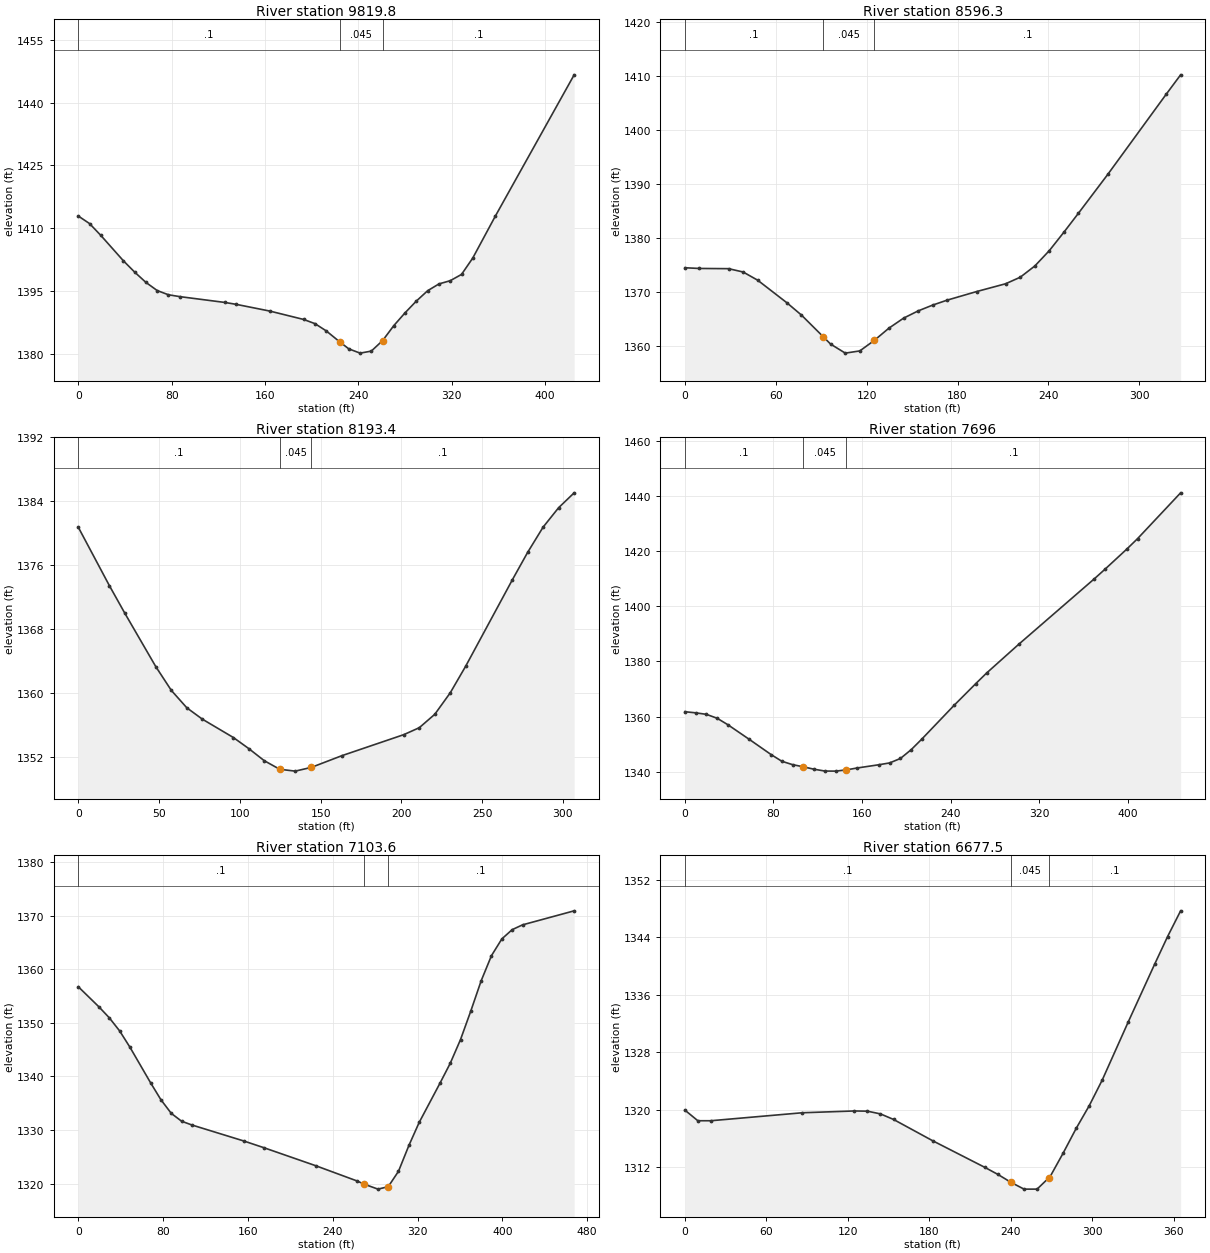
Type RM Length L Ch R = 1 ,9819.8  ,1220.7,1223.6,1226.4
XS GIS Cut Line= 2
     1935176.023      368100.134      1934962.71      368467.512
#Sta/Elev= 30
       0 1412.95     9.6 1411.16    19.3 1408.33    38.6 1402.29    48.3 1399.58
    57.9 1397.14    67.6 1395.19    77.2 1394.19    86.9 1393.75   125.5 1392.36
   135.2 1391.91   164.1  1390.3   193.1  1388.3   202.8  1387.3   212.4 1385.58
   224.2 1382.91   231.7  1381.3   241.4 1380.28     251 1380.76   260.7 1383.27
   270.3 1386.84     280 1389.91   289.6 1392.69   299.3 1395.16     309 1396.78
   318.6 1397.54   328.3 1399.04   337.9 1402.93   357.2  1412.9   424.8 1446.61
#Mann= 3 , 0 , 0
       0      .1       0   224.2    .045       0   260.7      .1       0
Bank Sta=224.2,260.7
XS Rating Curve= 0 ,0
Exp/Cntr=0.3,0.1

Type RM Length L Ch R = 1 ,8596.3  ,387.4,402.9,418.4
XS GIS Cut Line= 2
     1934139.069      367617.159     1933956.533      367888.738
#Sta/Elev= 27
       0  1374.5     9.6 1374.37    28.9 1374.33    38.5 1373.71    48.1 1372.19
    67.4    1368      77 1365.72    91.5 1361.67    96.2 1360.35   105.9 1358.67
   115.5 1359.08   125.1 1361.04   134.7  1363.3   144.4 1365.16     154  1366.5
   163.6 1367.58   173.2  1368.5   192.5 1370.08   211.7 1371.53   221.4 1372.75
     231 1374.83   240.6 1377.69   250.2  1381.1   259.8 1384.62   279.1  1391.8
   317.6 1406.64   327.2 1410.27
#Mann= 3 , 0 , 0
       0      .1       0    91.5    .045       0   125.1      .1       0
Bank Sta=91.5,125.1
XS Rating Curve= 0 ,0
Exp/Cntr=0.3,0.1

Type RM Length L Ch R = 1 ,8193.4  ,507.3,497.4,487.5
XS GIS Cut Line= 2
     1934027.766      367318.867     1933733.927      367407.909
#Sta/Elev= 24
       0 1380.72    19.2 1373.42    28.8 1369.95      48 1363.25    57.6 1360.28
    67.2  1358.1    76.8 1356.68      96 1354.38   105.5    1353   115.1 1351.48
   124.7  1350.4   134.3 1350.17   144.3 1350.64   163.1  1352.1   201.5 1354.74
   211.1 1355.61   220.7 1357.29   230.3 1359.99   239.9 1363.34   268.7 1374.13
   278.2 1377.58   287.8 1380.75   297.4 1383.18     307 1385.04
#Mann= 3 , 0 , 0
       0      .1       0   124.7    .045       0   144.3      .1       0
Bank Sta=124.7,144.3
XS Rating Curve= 0 ,0
Exp/Cntr=0.3,0.1

Type RM Length L Ch R = 1 ,7696    ,576.1,592.3,608.5
XS GIS Cut Line= 2
     1933662.693      366913.725     1933328.785      367212.016
#Sta/Elev= 29
       0 1361.76     9.7 1361.36    19.5 1360.81    29.2 1359.39    38.9 1357.04
    58.4 1351.69    77.9 1346.23    87.6  1343.8    97.3 1342.57   107.1 1341.78
   116.8  1340.9   126.5 1340.25   136.3 1340.22     146 1340.68   155.7 1341.36
   175.2 1342.53   184.9 1343.19   194.7 1344.81   204.4 1347.99   214.1 1351.87
   243.3 1364.13   262.8 1371.97   272.5 1375.78   301.7 1386.27   369.9 1409.99
   379.6 1413.49   399.1 1420.72   408.8  1424.5   447.7 1441.12
#Mann= 3 , 0 , 0
       0      .1       0   107.1    .045       0     146      .1       0
Bank Sta=107.1,146
XS Rating Curve= 0 ,0
Exp/Cntr=0.3,0.1

Type RM Length L Ch R = 1 ,7103.6  ,428.2,426.1,424
XS GIS Cut Line= 2
     1933649.337      366508.582     1933181.865      366521.939
#Sta/Elev= 30
       0 1356.75    19.5 1352.99    29.2 1350.96      39  1348.5    48.7 1345.46
    68.2 1338.81    77.9 1335.66    87.7 1333.11    97.4 1331.65   107.2 1330.94
   155.9 1327.97   175.4 1326.68   224.1 1323.33   263.1 1320.48   269.1 1319.94
   282.6 1318.97   292.3 1319.42     302  1322.3   311.8 1327.12   321.5 1331.42
     341  1338.7   350.8 1342.46   360.5 1346.89   370.2 1352.22     380 1357.88
   389.7 1362.56   399.5 1365.69   409.2 1367.41     419 1368.31   467.7 1370.93
#Mann= 3 , 0 , 0
       0      .1       0   269.1    .045       0   292.3      .1       0
Bank Sta=269.1,292.3
XS Rating Curve= 0 ,0
Exp/Cntr=0.3,0.1

Type RM Length L Ch R = 1 ,6677.5  ,250.8,239.6,227.8
XS GIS Cut Line= 2
     1933535.398      366081.905     1933172.961      366125.701
#Sta/Elev= 24
       0 1319.96     9.6 1318.47    19.2 1318.47    86.5 1319.58   124.9 1319.83
   134.5  1319.8   144.1 1319.42   153.7 1318.65   182.5 1315.69     221 1311.98
   230.6    1311   240.2  1309.9   249.8 1308.96   259.4 1308.96   267.9  1310.5
     269  1310.7   278.6 1313.97   288.2 1317.41   297.8 1320.56   307.4 1324.14
   326.6 1332.24   345.9 1340.21   355.5 1344.08   365.1 1347.66
#Mann= 3 , 0 , 0
       0      .1       0   240.2    .045       0   267.9      .1       0
Bank Sta=240.2,267.9
XS Rating Curve= 0 ,0
Exp/Cntr=0.3,0.1