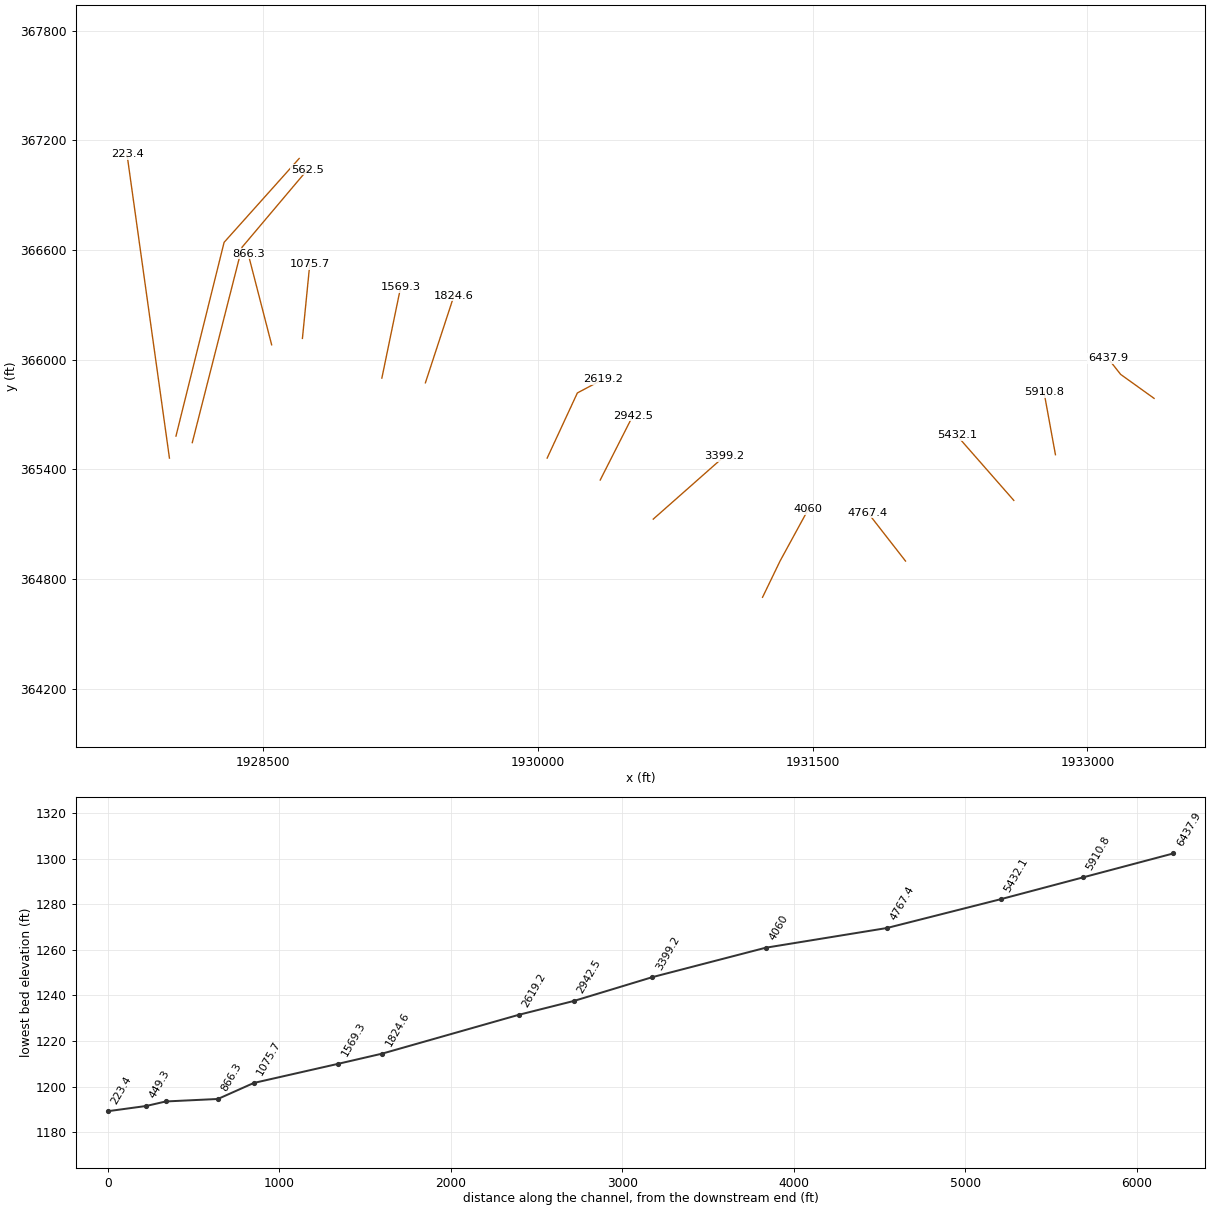
HEC-RAS study ROARINGCK.prj: ROARINGCK

--- ROARINGCK.g01 (geometry) --- (continued)

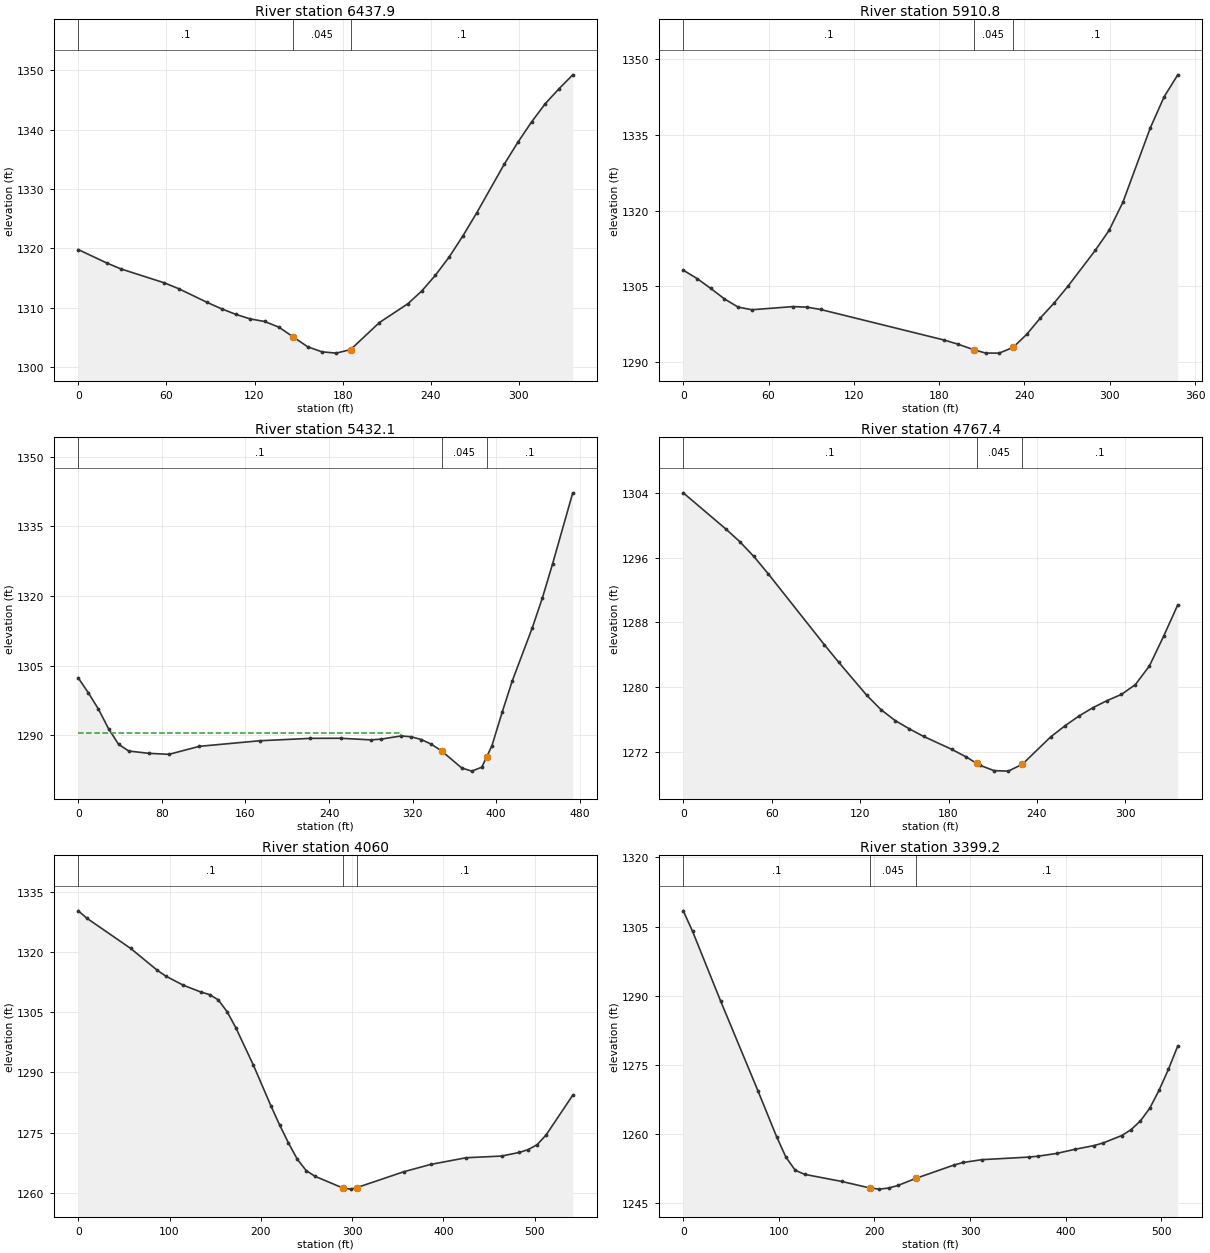
Type RM Length L Ch R = 1 ,6437.9  ,544.5,527.1,510.2
XS GIS Cut Line= 3
     1933363.957      365788.936     1933181.649      365919.971
     1933112.221       366008.12
#Sta/Elev= 29
       0 1319.78    19.5 1317.51    29.3  1316.5    58.6 1314.18    68.3  1313.2
    87.8 1310.88    97.6  1309.8   107.4 1308.86   117.1  1308.1   126.9 1307.67
   136.7  1306.7   146.4 1305.06   156.2 1303.41   165.9 1302.56   175.7 1302.34
   185.5 1302.95     205 1307.48   224.5 1310.67   233.9 1312.81   243.2 1315.46
   252.6 1318.54   261.9 1322.09   271.3 1325.96     290 1334.14   299.3 1337.84
   308.7 1341.29     318 1344.36   327.4 1346.88   336.7 1349.21
#Mann= 3 , 0 , 0
       0      .1       0   146.4    .045       0   185.5      .1       0
Bank Sta=146.4,185.5
XS Rating Curve= 0 ,0
Exp/Cntr=0.3,0.1

Type RM Length L Ch R = 1 ,5910.8  ,466.4,478.7,490.8
XS GIS Cut Line= 2
     1932825.763      365480.777     1932763.366      365822.957
#Sta/Elev= 25
       0 1308.22     9.7 1306.57    19.3 1304.62      29 1302.53    38.6 1300.92
    48.3  1300.4    77.3 1301.02      87 1300.91    96.6 1300.45   183.6  1294.4
   193.2 1293.59   204.2 1292.51   212.6 1291.84   222.2 1291.82   231.9 1292.94
   241.5 1295.51   251.2 1298.78   260.9 1301.75   270.5 1305.02   289.8 1312.14
   299.5 1316.09   309.2 1321.64   328.5 1336.35   338.2 1342.49   347.8 1346.84
#Mann= 3 , 0 , 0
       0      .1       0   204.2    .045       0   231.9      .1       0
Bank Sta=204.2,231.9
XS Rating Curve= 0 ,0
Exp/Cntr=0.3,0.1

Type RM Length L Ch R = 1 ,5432.1  ,666.2,664.7,663.2
XS GIS Cut Line= 2
     1932598.638      365230.826      1932286.99      365586.995
#Sta/Elev= 30
       0 1302.34     9.7 1299.12    19.3 1295.63      29  1291.4    38.6 1288.04
    48.3  1286.6    67.6  1286.1    86.9 1285.89   115.9 1287.61   173.8 1288.81
   222.2 1289.33   251.1 1289.35   280.1    1289   289.8 1289.16   309.1 1289.85
   318.7 1289.67   328.4 1289.07     338 1288.06   347.7 1286.63     367 1282.96
   376.7 1282.27   386.3 1283.13  390.851285.311     396 1287.78   405.7 1294.93
   415.3 1301.63   434.6 1313.16   444.3 1319.62     454 1326.91   473.3  1342.2
#Mann= 3 , 0 , 0
       0      .1       0   347.7    .045       0  390.85      .1       0
#XS Ineff= 2 , 0
          308.45 1290.43
Permanent Ineff=
       F       F
Bank Sta=347.7,390.85
XS Rating Curve= 0 ,0
Exp/Cntr=0.3,0.1

Type RM Length L Ch R = 1 ,4767.4  ,733.4,707.3,680.9
XS GIS Cut Line= 2
      1932007.62      364899.179      1931801.71      365164.044
#Sta/Elev= 29
       0 1304.02    28.8 1299.56    38.3 1297.99    47.9 1296.15    57.5 1294.04
    95.8 1285.22   105.4 1283.08   124.6 1278.96   134.2  1277.2   143.8 1275.85
   153.4 1274.83     163  1273.9   182.1  1272.3   191.7 1271.38     199 1270.57
   201.3 1270.32   210.9 1269.66   220.5  1269.6     230 1270.44   249.2 1273.82
   258.8 1275.18   268.4 1276.41     278 1277.45   287.6 1278.33   297.2 1279.08
   306.7 1280.29   316.3 1282.62   325.9 1286.28   335.5 1290.16
#Mann= 3 , 0 , 0
       0      .1       0     199    .045       0     230      .1       0
Bank Sta=199,230
XS Rating Curve= 0 ,0
Exp/Cntr=0.3,0.1

Type RM Length L Ch R = 1 ,4060    ,668.2,660.8,653.4
XS GIS Cut Line= 3
     1931227.387      364701.025     1931323.151       364899.74
     1931476.705      365181.853
#Sta/Elev= 30
       0 1330.27     9.6  1328.4    57.5 1320.89    86.3 1315.51    95.9    1314
   115.1 1311.74   134.3 1310.05   143.9  1309.4   153.4 1308.09     163 1305.17
   172.6 1301.17   191.8 1291.87     211 1281.73   220.6 1276.94   230.3 1272.45
     240 1268.38   249.8 1265.54   259.5 1264.13   290.1  1261.2   298.4 1260.94
   305.1 1261.31   356.8 1265.28     386 1267.09     425 1268.76   463.9 1269.18
   483.4 1270.09   493.1  1270.8   502.8 1272.01   512.6 1274.43   541.8 1284.34
#Mann= 3 , 0 , 0
       0      .1       0   290.1    .045       0   305.1      .1       0
Bank Sta=290.1,305.1
XS Rating Curve= 0 ,0
Exp/Cntr=0.3,0.1

Type RM Length L Ch R = 1 ,3399.2  ,448.1,456.7,465.3
XS GIS Cut Line= 2
     1930630.804      365128.427     1931018.138       365471.24
#Sta/Elev= 30
       0 1308.41     9.8 1303.93      39 1288.88    78.1 1269.37    97.6 1259.43
   107.4 1254.96   117.1 1252.13   126.9 1251.24   165.9 1249.69   195.2 1248.28
     205 1248.03   214.7 1248.26   224.5 1248.82   243.1 1250.35     283 1253.25
   292.8 1253.81   312.3 1254.42   361.1 1254.98   370.9 1255.17   390.4 1255.77
   409.9 1256.68   429.4 1257.47   439.2 1258.05   458.7 1259.66   468.4 1260.93
   478.2 1262.84     488 1265.61   497.7 1269.51   507.5 1274.04   517.2 1279.09
#Mann= 3 , 0 , 0
       0      .1       0   195.2    .045       0   243.1      .1       0
Bank Sta=195.2,243.1
XS Rating Curve= 0 ,0
Exp/Cntr=0.3,0.1

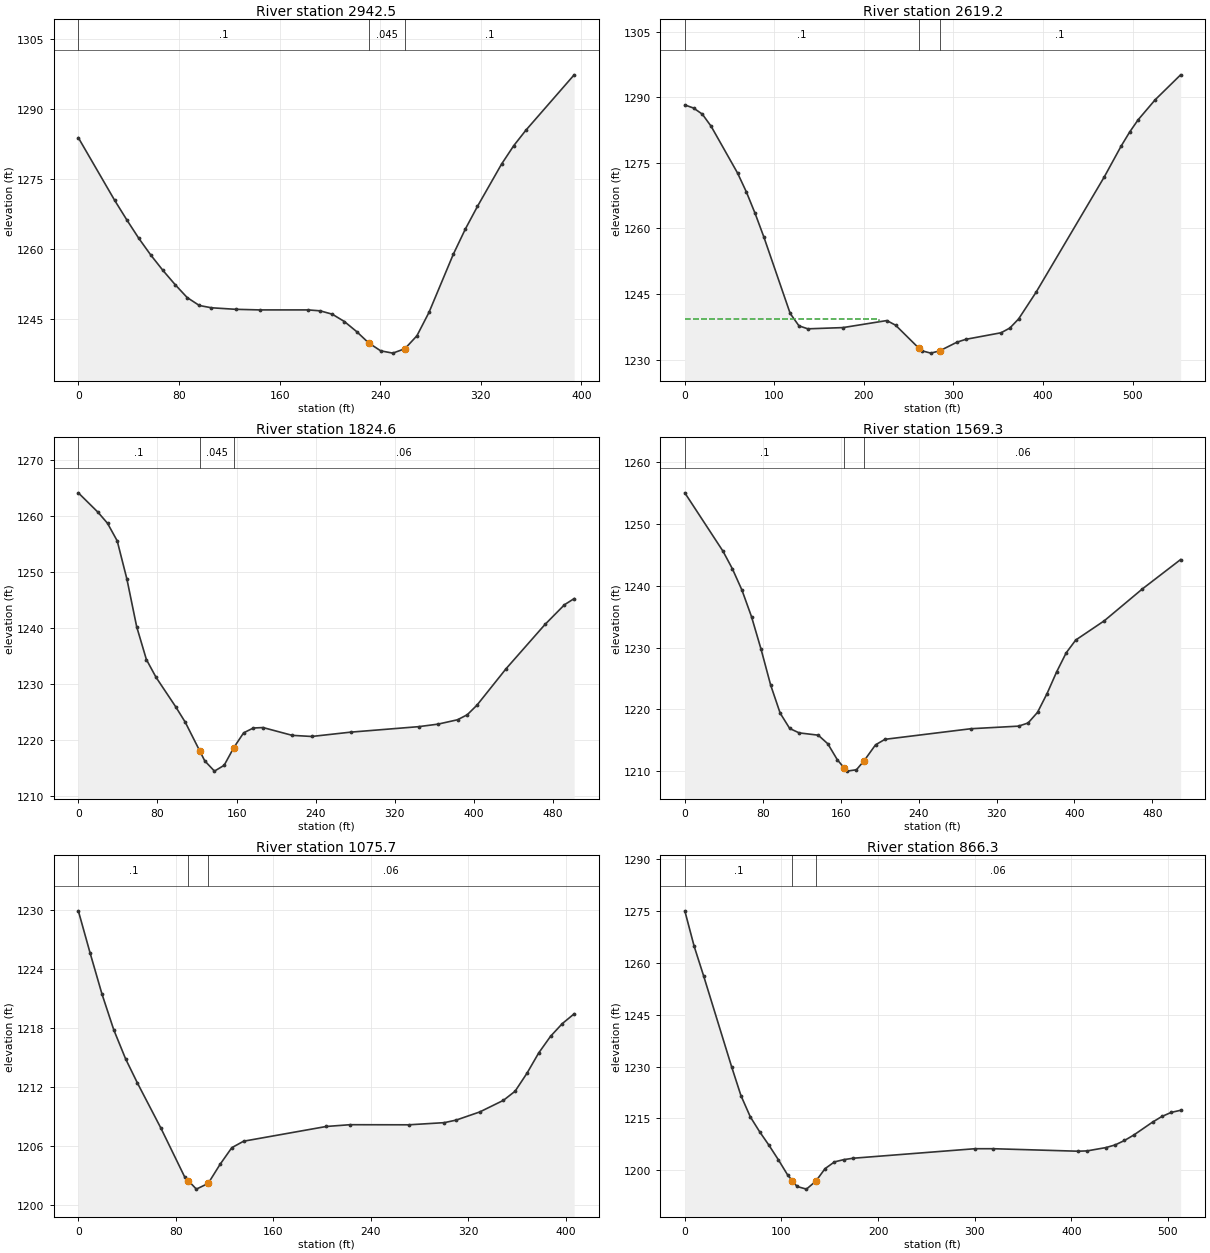
Type RM Length L Ch R = 1 ,2942.5  ,322.4,323.3,324.1
XS GIS Cut Line= 2
     1930341.417      365342.129     1930519.501      365693.846
#Sta/Elev= 30
       0 1283.86    28.8 1270.45    38.5 1266.23    48.1 1262.24    57.7 1258.63
    67.3 1255.35    76.9 1252.33    86.5 1249.54    96.2 1247.83   105.8 1247.34
     125 1247.01   144.2 1246.88   182.7 1246.88   192.3 1246.68   201.9 1245.96
   211.5 1244.39   221.2 1242.24   230.8  1239.8   240.4 1238.09     250  1237.6
   259.6 1238.54   269.2 1241.33   278.8 1246.36   298.1 1258.82   307.7 1264.25
   317.3  1269.1   336.5  1278.2   346.2 1282.16   355.8 1285.46   394.2 1297.36
#Mann= 3 , 0 , 0
       0      .1       0   230.8    .045       0   259.6      .1       0
Bank Sta=230.8,259.6
XS Rating Curve= 0 ,0
Exp/Cntr=0.3,0.1

Type RM Length L Ch R = 1 ,2619.2  ,791.9,794.7,797.2
XS GIS Cut Line= 3
     1930052.029      365462.336     1930216.757      365818.505
     1930359.225      365894.191
#Sta/Elev= 30
       0 1288.25     9.8 1287.54    19.6 1286.14    29.4 1283.37    58.9 1272.68
    68.7 1268.38    78.5 1263.45    88.3 1258.04   117.7 1240.55   127.5 1237.72
   137.4 1237.04   176.6 1237.32   225.6 1238.93   235.4 1237.87   261.1 1232.67
   264.9 1232.01   274.7 1231.48   284.5 1231.99   304.1    1234   313.9 1234.64
   353.2 1236.14     363 1237.22   372.8 1239.31   392.4 1245.45   468.3 1271.74
   487.3 1278.85   496.8 1282.06   506.3 1284.87   525.3 1289.44   553.7 1295.14
#Mann= 3 , 0 , 0
       0      .1       0   261.1    .045       0   284.5      .1       0
#XS Ineff= 2 , 0
          216.34 1239.27
Permanent Ineff=
       F       F
Bank Sta=261.1,284.5
XS Rating Curve= 0 ,0
Exp/Cntr=0.3,0.1

Type RM Length L Ch R = 1 ,1824.6  ,252.7,255.3,257.8
XS GIS Cut Line= 2
     1929387.501      365873.877     1929543.325      366350.253
#Sta/Elev= 30
       0 1264.11    19.7 1260.68    29.5 1258.68    39.3 1255.54    49.1 1248.73
      59 1240.22    68.8 1234.38    78.6  1231.2    98.3 1225.99   108.1  1223.2
   122.8 1218.06   127.8 1216.31   137.6 1214.48   147.4 1215.52   157.2 1218.69
   167.1 1221.31   176.9 1222.17   186.7 1222.25   216.2 1220.86   235.9 1220.66
   275.2 1221.43     344 1222.41   363.6 1222.86   383.3 1223.64   393.1 1224.53
   402.9 1226.23   432.4 1232.75   471.7 1240.63   491.4 1244.15   501.2 1245.25
#Mann= 3 , 0 , 0
       0      .1       0   122.8    .045       0   157.2     .06       0
Bank Sta=122.8,157.2
XS Rating Curve= 0 ,0
Exp/Cntr=0.3,0.1

Type RM Length L Ch R = 1 ,1569.3  ,491.5,493.6,496
XS GIS Cut Line= 2
     1929149.907      365899.538     1929252.655      366398.014
#Sta/Elev= 30
       0    1255    39.2 1245.57    48.9 1242.71    58.7 1239.27    68.5 1234.98
    78.3 1229.72    88.1 1223.96    97.9  1219.4   107.7 1216.92   117.4 1216.21
     137 1215.84   146.8 1214.45   156.6 1211.86   163.31210.608   166.4 1210.03
   176.2 1210.25   184.21211.736   195.8 1214.28   205.5 1215.17   293.6 1216.88
   342.6  1217.3   352.4 1217.81   362.1 1219.53   371.9 1222.57   381.7 1226.06
   391.5 1229.14   401.3 1231.21   430.6 1234.32   469.8 1239.48     509 1244.22
#Mann= 3 , 0 , 0
       0      .1       0   163.3    .045       0   184.2     .06       0
Bank Sta=163.3,184.2
XS Rating Curve= 0 ,0
Exp/Cntr=0.3,0.1

Type RM Length L Ch R = 1 ,1075.7  ,201.4,209.4,217.2
XS GIS Cut Line= 2
     1928716.395      366116.797     1928756.464      366521.939
#Sta/Elev= 27
       0 1229.94     9.7 1225.63    19.4 1221.47    29.1 1217.82    38.8 1214.87
    48.5 1212.41    67.8 1207.81    87.2 1202.87    90.3 1202.46    96.9  1201.6
   106.6 1202.18   116.3 1204.11     126 1205.82   135.7 1206.48   203.6 1207.98
     223 1208.16   271.4 1208.15   300.5 1208.37   310.2 1208.63   329.6 1209.46
     349 1210.64   358.6 1211.57   368.4 1213.41     378 1215.47   387.7 1217.16
   397.4 1218.46   407.1 1219.45
#Mann= 3 , 0 , 0
       0      .1       0    90.3    .045       0   106.6     .06       0
Bank Sta=90.3,106.6
XS Rating Curve= 0 ,0
Exp/Cntr=0.3,0.1

Type RM Length L Ch R = 1 ,866.3   ,317.5,303.8,290.2
XS GIS Cut Line= 2
     1928548.419      366081.905     1928420.381      366578.867
#Sta/Elev= 30
       0 1275.01     9.7 1264.75    19.4 1256.28    48.4    1230    58.1 1221.62
    67.8 1215.47    77.5 1211.14    87.2 1207.22    96.8 1203.08   106.5 1198.64
   111.4 1196.97   116.2 1195.33   125.9 1194.57   135.6 1196.86   145.2  1200.5
   154.9 1202.44   164.6  1203.1   174.3  1203.5   300.2 1206.25   319.5 1206.25
   406.7 1205.53   416.4 1205.62   435.7 1206.57   445.4 1207.34   455.1 1208.63
   464.8 1210.22   484.1 1213.93   493.8 1215.57   503.5 1216.75   513.2 1217.36
#Mann= 3 , 0 , 0
       0      .1       0   111.4    .045       0   135.6     .06       0
Bank Sta=111.4,135.6
XS Rating Curve= 0 ,0
Exp/Cntr=0.3,0.1

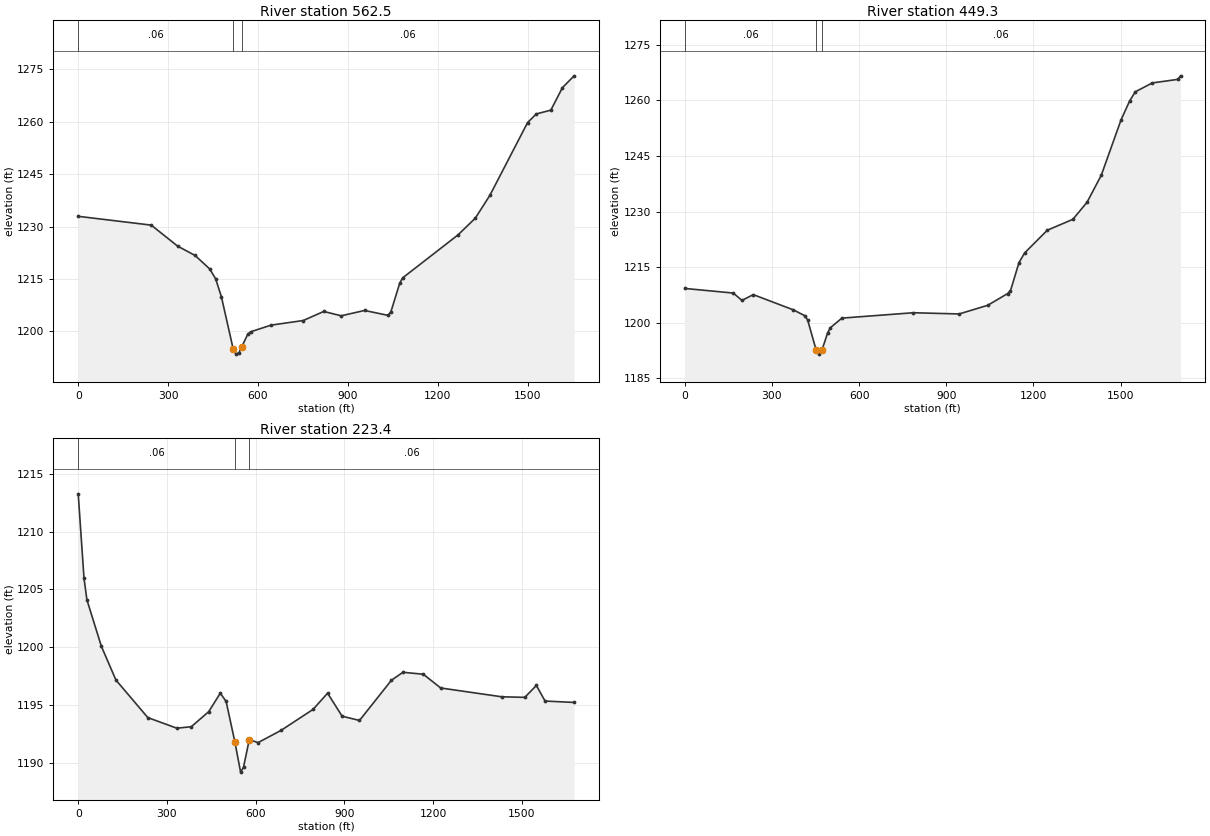
Type RM Length L Ch R = 1 ,562.5   ,111.4,113.2,114.5
XS GIS Cut Line= 3
      1928115.36      365546.926     1928386.939      366615.433
     1928743.108      367038.384
#Sta/Elev= 30
       0 1232.92   243.9  1230.4   331.7  1224.4   390.3 1221.71     439 1217.86
   458.6 1215.07   478.1 1209.87   517.1 1195.06   526.8 1193.48   536.6 1193.87
   546.4 1195.65   565.9 1199.14   575.6 1199.87   643.9 1201.78   751.2  1203.1
   819.5 1205.69   878.1 1204.45   956.1 1205.98  1034.2 1204.57  1043.9 1205.62
  1073.2 1213.75    1083  1215.3  1267.4 1227.57  1325.6 1232.39  1374.1  1238.9
  1500.2 1259.76  1529.3 1262.22  1577.8 1263.31  1616.6 1269.75  1655.4 1273.13
#Mann= 3 , 0 , 0
       0     .06       0   517.1    .045       0   546.4     .06       0
Bank Sta=517.1,546.4
XS Rating Curve= 0 ,0
Exp/Cntr=0.3,0.1

Type RM Length L Ch R = 1 ,449.3   ,216.4,225.8,235.3
XS GIS Cut Line= 3
     1928026.318      365582.543     1928288.992      366642.146
     1928698.587      367100.714
#Sta/Elev= 30
       0 1209.24   167.2 1207.99   196.7 1206.01     236 1207.57   373.7 1203.46
   413.1 1201.88   422.9 1200.75   452.4 1192.57   462.2 1191.51   472.1 1192.56
   491.8 1197.26   501.6 1198.66   540.9 1201.23   786.8 1202.68   944.2 1202.35
  1042.5 1204.68  1111.2 1207.85    1121  1208.6  1150.2  1216.2  1169.8 1218.83
  1247.8 1224.96  1335.7 1227.89  1384.5  1232.5  1433.3 1239.76  1501.6 1254.75
  1530.9 1259.81  1550.4  1262.3  1608.9  1264.7  1696.8 1265.66  1706.5 1266.62
#Mann= 3 , 0 , 0
       0     .06       0   452.4    .045       0   472.1     .06       0
Bank Sta=452.4,472.1
XS Rating Curve= 0 ,0
Exp/Cntr=0.3,0.1

Type RM Length L Ch R = 1 ,223.4   ,212.2,223.4,234
XS GIS Cut Line= 2
     1927990.701      365462.336     1927759.191      367122.974
#Sta/Elev= 30
       0 1213.27    19.6 1205.97    29.4  1204.1    78.4 1200.07   127.5 1197.16
   235.3 1193.91   333.4 1192.99   382.4 1193.12   441.2 1194.42   480.5 1196.02
   500.1 1195.31   529.5 1191.83   549.1 1189.19   558.9 1189.61   578.5 1192.01
   607.9 1191.74   686.4 1192.81   794.2 1194.62   843.2 1196.02   892.3 1194.03
   951.1 1193.66    1059 1197.14  1098.2 1197.83  1166.8 1197.66  1225.7 1196.47
  1431.6 1195.71    1510 1195.66  1549.2 1196.69  1578.6 1195.34  1676.7 1195.22
#Mann= 3 , 0 , 0
       0     .06       0   529.5    .045       0   578.5     .06       0
Bank Sta=529.5,578.5
XS Rating Curve= 0 ,0
Exp/Cntr=0.3,0.1

Chan Stop Cuts=-1
Use User Specified Reach Order=0
Composite Channel Slope=5